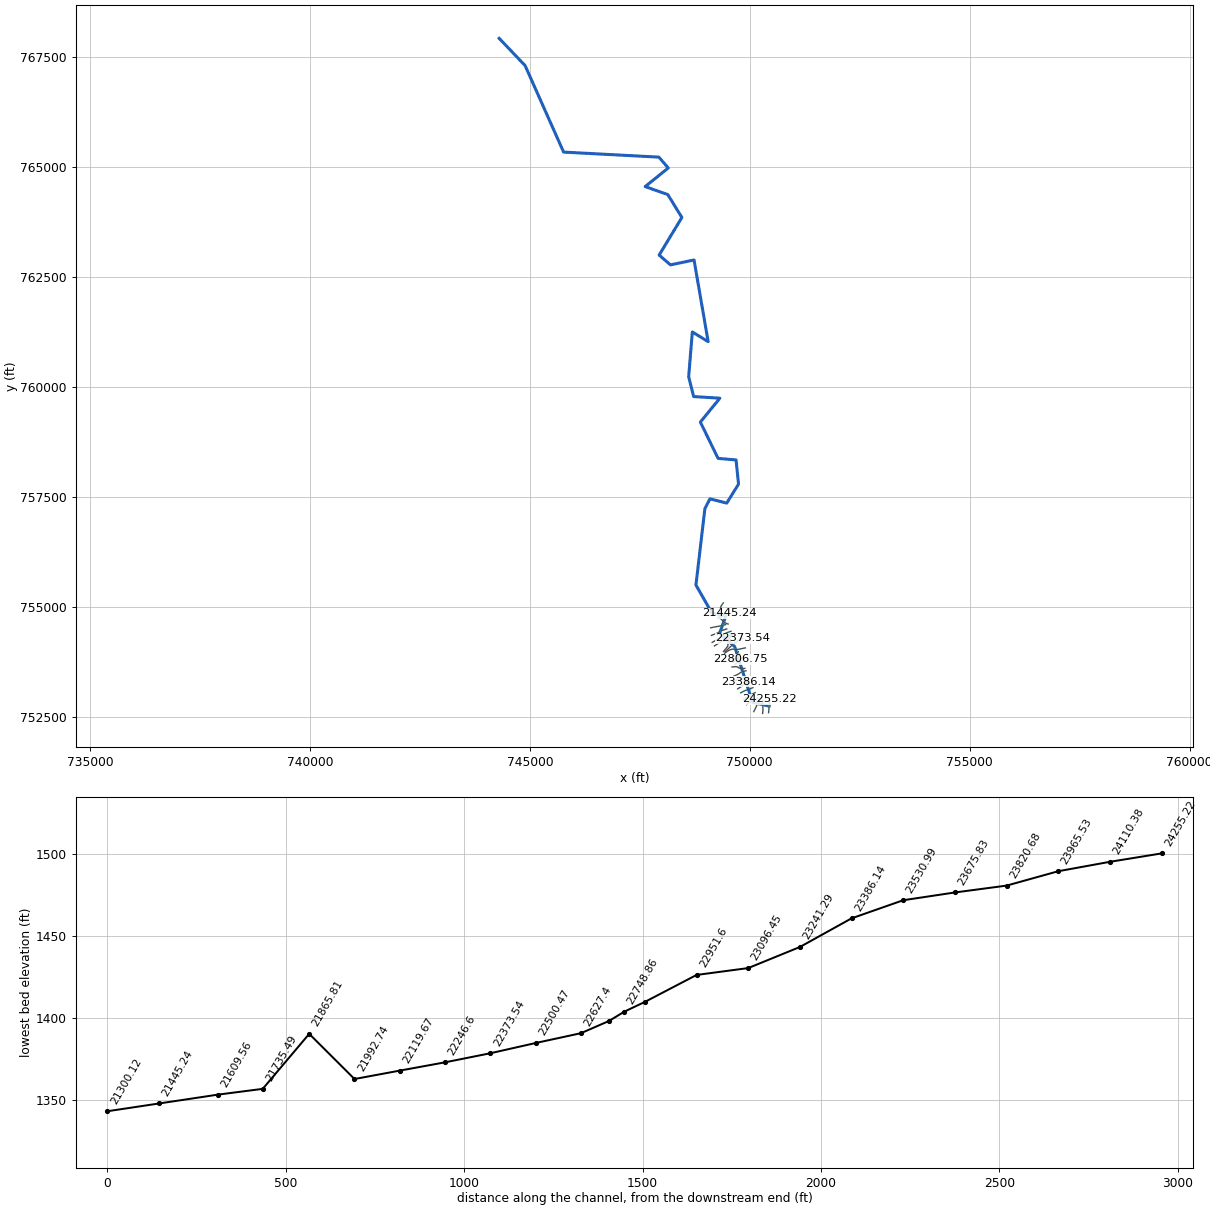
--- 14313_ras.prj (project) ---

Proj Title=14313
Current Plan=p01
Default Exp/Contr=0.3,0.1
English Units
Geom File=g01
Flow File=f01
Plan File=p01
Y Axis Title=Elevation
X Axis Title(PF)=Main Channel Distance
X Axis Title(XS)=Station
BEGIN DESCRIPTION:
RFD model 14313 exported to HEC-RAS
END DESCRIPTION:

--- 14313_ras.p01 (plan) ---

Plan Title=Plan 01
Program Version=4.10
Short Identifier=Plan 01
Geom File=g01
Flow File=f01
Subcritical Flow
Calc Critical at every XS
Secant Critical Depth

--- 14313_ras.f01 (steady flow) ---

Flow Title=Flow 01
Program Version=5.01
Number of Profiles= 6
Profile Names=10yr,25yr,50yr,100yr,100plus,500yr
River Rch & RM=14313,111,24255.22
  686.28 1130.25 1556.76 1956.93 2857.12 4180.15
River Rch & RM=14313,111,24110.38
  689.47 1135.67 1564.39  1966.7 2871.38 4198.86
River Rch & RM=14313,111,23965.53
  691.43 1139.01 1569.08 1972.71 2880.15 4210.36
River Rch & RM=14313,111,23820.68
  719.49  1186.5 1635.71 2057.73 3004.29 4371.52
River Rch & RM=14313,111,23675.83
   720.7 1188.56 1638.61 2061.45 3009.72 4378.59
River Rch & RM=14313,111,23530.99
   725.8 1197.23 1650.81 2077.06 3032.51 4408.27
River Rch & RM=14313,111,23386.14
   728.7 1202.17 1657.77 2085.97 3045.51 4425.19
River Rch & RM=14313,111,23241.29
  733.44 1210.28 1669.22 2100.67 3066.98 4453.33
River Rch & RM=14313,111,23096.45
  735.01 1213.01 1673.12 2105.72 3074.35 4463.17
River Rch & RM=14313,111, 22951.6
  749.96 1238.91 1709.97 2153.34 3143.88 4555.48
River Rch & RM=14313,111,22806.75
  754.45 1246.69 1721.06 2167.68 3164.82  4583.3
River Rch & RM=14313,111,22706.42
  757.98 1252.84 1729.85 2179.09 3181.46 4605.52
River Rch & RM=14313,111,22500.47
  759.73 1255.91 1734.24 2184.77 3189.77 4616.61
River Rch & RM=14313,111,22373.54
  767.01 1268.59 1752.34 2208.25 3224.04 4662.25
River Rch & RM=14313,111, 22246.6
  768.55 1271.27 1756.18 2213.22  3231.3 4671.91
River Rch & RM=14313,111,22119.67
   770.3 1274.33 1760.55 2218.89 3239.58 4682.94
River Rch & RM=14313,111,21992.74
  772.71 1278.54 1766.56 2226.68 3250.96 4698.09
River Rch & RM=14313,111,21865.81
  775.96 1284.22  1774.7 2237.26  3266.4 4718.71
River Rch & RM=14313,111,21735.49
  776.62 1285.37 1776.34 2239.39 3269.51 4722.83
River Rch & RM=14313,111,21609.56
  780.55 1292.23 1786.14  2252.1 3288.07 4747.53
River Rch & RM=14313,111,21300.12
  782.39  1295.5 1790.88 2258.31 3297.13 4759.86
River Rch & RM=14313,111,   21155
  786.57 1302.89 1801.52 2272.21 3317.42 4787.21
River Rch & RM=14313,111,21009.88
  787.37 1304.33 1803.61 2274.94 3321.42 4792.68
River Rch & RM=14313,111,20864.75
  788.96 1307.18 1807.75  2280.4 3329.38  4803.6
River Rch & RM=14313,111,20574.51
   791.7 1312.12 1814.95 2289.89 3343.24 4822.68
River Rch & RM=14313,111,20456.51
  792.49 1313.53 1817.01  2292.6  3347.2 4828.13
River Rch & RM=14313,111,20284.26
 1002.81 1678.41 2337.05  2965.5 4329.63 6097.39
River Rch & RM=14313,111,20139.14
 1005.24 1682.78 2343.41 2973.87 4341.85 6113.54
River Rch & RM=14313,111,19994.02
 1009.91 1691.15 2355.59 2989.92 4365.28 6144.53
River Rch & RM=14313,111, 19848.9
 1010.84 1692.82 2358.02 2993.12 4369.96 6150.72
River Rch & RM=14313,111,19703.77
 1011.96 1694.83 2360.95 2996.97 4375.58 6158.15
River Rch & RM=14313,111,19558.65
 1016.05 1702.18 2371.64 3011.06 4396.15 6185.35
River Rch & RM=14313,111,19413.53
 1021.72  1712.3 2386.33 3030.37 4424.35 6222.37
River Rch & RM=14313,111, 19268.4
  1022.8 1714.26  2389.2 3034.16 4429.88 6229.76
River Rch & RM=14313,111,19160.83
 1023.86  1716.2 2392.05 3037.94  4435.4 6237.15
River Rch & RM=14313,111,19093.66
  1039.4  1744.2  2432.9 3091.89 4514.16 6341.47
River Rch & RM=14313,111,18833.04
 1040.46 1746.14 2435.74 3095.65 4519.65 6348.81
River Rch & RM=14313,111,18687.91
 1046.64 1757.29 2452.01 3117.15 4551.03 6390.33
River Rch & RM=14313,111,18542.79
 1047.53  1758.9 2454.38 3120.28 4555.61 6396.43
River Rch & RM=14313,111,18397.67
 1049.83 1763.09 2460.52 3128.42 4567.49 6412.27
River Rch & RM=14313,111,18252.55
 1050.36 1764.05 2461.93 3130.29 4570.23 6415.92
River Rch & RM=14313,111,18063.14
 1052.13 1767.27 2466.65 3136.55 4579.37 6428.09
River Rch & RM=14313,111,17555.41
 1055.69 1773.72  2476.1 3149.07 4597.65 6452.41
River Rch & RM=14313,111,17408.78
 1067.36 1794.93 2507.18 3190.27 4657.79 6532.41
River Rch & RM=14313,111,17176.29
 1068.24 1796.53 2509.54 3193.39 4662.35 6538.45
River Rch & RM=14313,111,17112.03
  1338.2 2269.77  3188.9 4077.93 5953.78 8153.46
River Rch & RM=14313,111,17007.41
 1339.36 2271.89 3192.01 4082.06 5959.81 8161.21
River Rch & RM=14313,111,16748.67
 1342.51 2277.62 3200.44 4093.25 5976.14 8182.25
River Rch & RM=14313,111, 16461.5
 1347.81 2287.27 3214.61 4112.08 6003.63 8217.64
River Rch & RM=14313,111,16217.75
 1358.29 2306.31 3242.55 4149.15 6057.77 8287.13
River Rch & RM=14313,111,15974.01
 1382.88 2351.07 3308.27 4236.43 6185.18 8450.59
River Rch & RM=14313,111,15730.26
    1386 2356.75 3316.63 4247.52 6201.38 8471.35
River Rch & RM=14313,111,15486.52
 1387.32 2359.14 3320.14 4252.19 6208.19 8480.08
River Rch & RM=14313,111,15242.77
 1388.96 2362.13 3324.53 4258.02 6216.71 8490.99
River Rch & RM=14313,111,14780.35
 1410.91  2402.1 3383.25 4336.02 6330.58 8636.67
River Rch & RM=14313,111,14511.53
 1687.31 2890.64 4088.61 5258.92 7678.0210273.66
River Rch & RM=14313,111,14267.79
 1691.22 2897.77 4099.09 5272.84 7698.3510298.95
River Rch & RM=14313,111,14024.04
 1700.79 2915.17 4124.66 5306.82 7747.9510360.56
River Rch & RM=14313,111, 13780.3
 1702.83 2918.88 4130.11 5314.06 7758.5310373.67
River Rch & RM=14313,111,13481.62
 1706.29 2925.16 4139.34 5326.31 7776.4110395.85
River Rch & RM=14313,111,13292.81
 1708.02  2928.3 4143.95 5332.43 7785.3510406.93
River Rch & RM=14313,111, 12975.3
 2097.05 3628.13 5165.84 6682.68 9756.7112780.41
River Rch & RM=14313,111,12778.41
 2098.86 3631.41 5170.64 6689.06 9766.0312791.56
River Rch & RM=14313,111,12561.57
  2100.5  3634.4 5175.04 6694.89 9774.5512801.77
River Rch & RM=14313,111,12317.82
 2107.23 3646.62 5192.99 6718.74 9809.3612843.52
River Rch & RM=14313,111,12074.08
 2110.07 3651.78 5200.56  6728.8 9824.0512861.13
River Rch & RM=14313,111,11830.33
  2100.8 3634.95 5175.84 6695.95 9776.0912803.63
River Rch & RM=14313,111,11586.59
 2110.07 3651.78 5200.56  6728.8 9824.0512861.13
River Rch & RM=14313,111,11342.84
 2114.71 3660.19 5212.92 6745.21 9848.0112889.85
River Rch & RM=14313,111,11099.09
 2116.95 3664.26  5218.9 6753.15  9859.612903.73
River Rch & RM=14313,111, 10878.5
 2125.47 3679.73 5241.62 6783.31 9903.6412956.44
River Rch & RM=14313,111, 10611.6
 2132.04 3691.65 5259.13 6806.57 9937.5912997.07
River Rch & RM=14313,111,10367.86
 2134.87 3696.79 5266.68  6816.6 9952.24 13014.6
River Rch & RM=14313,111,10124.11
 2141.88 3709.51 5285.36 6841.42 9988.4713057.92
River Rch & RM=14313,111,9880.366
 2144.56 3714.38 5292.51 6850.9110002.33 13074.5
River Rch & RM=14313,111,9636.621
 2146.35 3717.63 5297.28 6857.2410011.5813085.55
River Rch & RM=14313,111,9392.875
 2147.54 3719.79 5300.46 6861.4610017.7413092.91
River Rch & RM=14313,111,9149.129
 2161.08 3744.37 5336.57 6909.4210087.7613176.54
River Rch & RM=14313,111,8905.384
 2162.12 3746.26 5339.34 6913.1110093.1413182.97
River Rch & RM=14313,111,8661.638
 2197.19 3809.98 5432.99 7037.53 10274.813399.77
River Rch & RM=14313,111,8417.893
    2200 3815.09 5440.48 7047.4910289.3413417.09
River Rch & RM=14313,111,8174.147
 2202.08 3818.85 5446.01 7054.8310300.0613429.85
River Rch & RM=14313,111,7930.401
 2204.45 3823.15 5452.33 7063.2210312.3113444.42
River Rch & RM=14313,111,7686.656
 2459.32  4285.3 6130.84 7963.9611627.3914993.79
River Rch & RM=14313,111, 7442.91
  2465.1 4295.78 6146.23 7984.4111657.2315028.68
River Rch & RM=14313,111,7137.776
 2468.13 4301.28 6154.31 7995.1311672.8915046.98
River Rch & RM=14313,111,6896.264
 2470.01 4304.69 6159.31 8001.7711682.59 15058.3
River Rch & RM=14313,111,6654.751
 2475.33 4314.36 6173.52 8020.6511710.1515090.52
River Rch & RM=14313,111,6413.238
 2478.06 4319.31  6180.8 8030.3311724.2815107.05
River Rch & RM=14313,111,6171.725
 2478.78 4320.62 6182.72 8032.88   11728 15111.4
River Rch & RM=14313,111,5930.213
 2480.22 4323.24 6186.56 8037.9811735.4515120.09
River Rch & RM=14313,111,  5688.7
 2490.46  4341.8 6213.83 8074.1911788.3215181.79
River Rch & RM=14313,111,5447.188
 2492.19 4344.94 6218.44 8080.3111797.25 15192.2
River Rch & RM=14313,111, 4722.65
 2478.06 4319.31  6180.8 8030.3311724.2815107.05
Boundary for River Rch & Prof#=14313,111,1
Up Type= 0
Dn Type= 2
Boundary for River Rch & Prof#=14313,111,2
Up Type= 0
Dn Type= 2
Boundary for River Rch & Prof#=14313,111,2
Up Type= 0
Dn Type= 2
Boundary for River Rch & Prof#=14313,111,2
Up Type= 0
Dn Type= 2
Boundary for River Rch & Prof#=14313,111,2
Up Type= 0
Dn Type= 2
Boundary for River Rch & Prof#=14313,111,2
Up Type= 0
Dn Type= 2

--- 14313_ras.g01 (geometry) ---

Geom Title=14313
Program Version=4.10

River Reach=14313,111
Reach XY= 30
 750440.91405642752739.067147732750063.830723107752823.789369985
749656.261278689754094.192147747749315.427945346754391.692147747
749457.927945346754796.692147732749143.344611973754850.858814403
748776.955723077755491.275481075748980.136278689757229.303258851
749095.761278689757451.872703299 749476.66405642 757354.65048106
749745.424301267757786.366073504 749689.16405642758336.594925523
749279.719612002758371.803258851748877.643565238759197.635392353
749320.969612002759740.206036612748724.719611973759777.289369971
748611.594611973760226.664369956 748694.78905645761246.626175508
749054.641487002 761026.00985606 748733.96093145762882.745967194
748197.502598077762772.120967194747940.349820316762994.620967194
748456.877598077 763849.62096718748137.814710647764369.558560431
 747622.71093142764552.607078299 748147.71093142764975.107078299
747933.714004278765221.859670579 745768.18041417765336.276678115
 744891.44441992767305.026636899744301.823183894767923.185900196

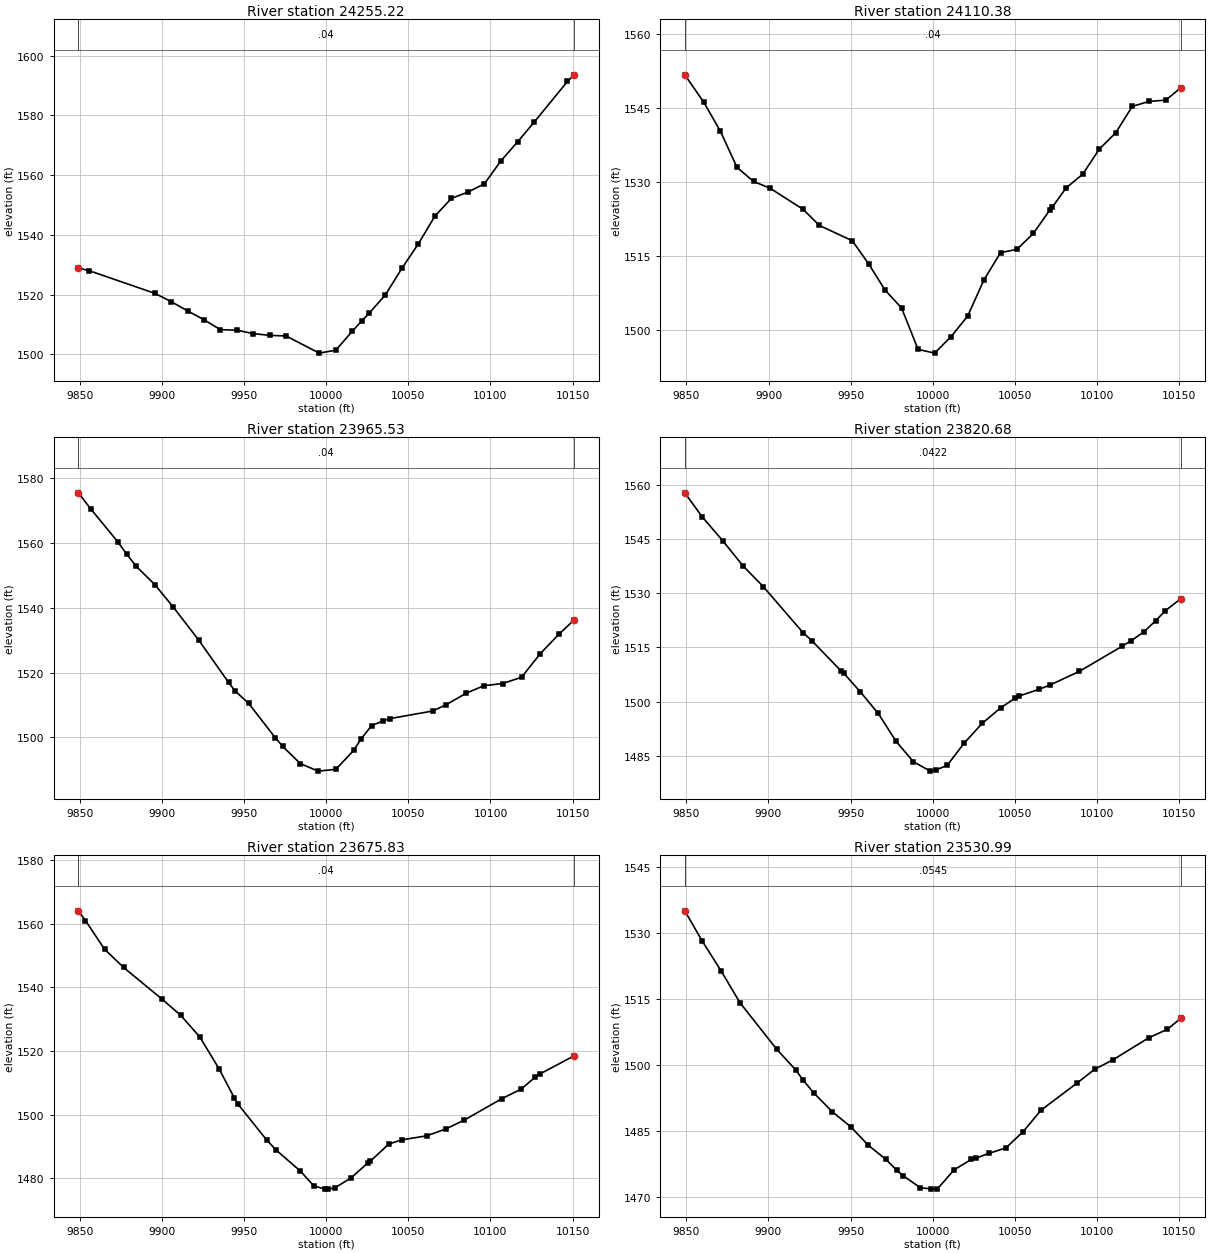
Type RM Length L Ch R = 1 ,24255.22,144.847200,144.847200,144.847200
XS GIS Cut Line= 6
750428.957992893752588.729534924750433.897927832752643.340667143
750437.635928973752722.778814566750443.003556186752760.813867483
750451.032929206752844.741459969750458.234723084752889.036159002
#Sta/Elev= 28
9849.0191528.9119855.3151528.0619895.4781520.4459905.5141517.6659915.5251514.548
9925.5361511.5899935.5481508.2569945.5591508.085 9955.571506.9289965.5811506.355
9975.5921506.1359995.7151500.39810005.821501.38410015.921507.75110021.791511.294
   100261513.67110036.041519.92510046.091528.79710056.13 1537.0310066.181546.281
10076.231552.22710086.27 1554.3110096.321557.10810106.371564.771 10116.51571.129
10126.631577.73510146.891591.36710150.981593.591
#Mann= 3 , 0 , 0
9849.019    0.04       09849.019    0.04       010150.98    0.04       0
#XS Ineff= 2 , 0
       0                               0
Bank Sta=9849.019,10150.98
Exp/Cntr=0.3,0.1

Type RM Length L Ch R = 1 ,24110.38,144.847300,144.847300,144.847300
XS GIS Cut Line= 6
750292.987616888752573.430297966750298.765306231752621.861609358
750300.654461604752664.614417055750293.502448887752796.494040899
750297.307760826752840.139579966750303.613749378 752873.91898091
#Sta/Elev= 30
9849.0331551.7259860.6851546.1159870.7561540.2629880.8271532.9529890.8981530.098
 9900.951528.7239920.9691524.4739930.9791521.1779950.993 1518.089960.9991513.379
9971.0041508.0599981.0221504.4369991.0731496.04610001.131495.28210011.181498.634
10021.221502.77410031.261510.16710041.281515.65910051.281516.32910061.281519.559
10071.281524.29410072.771524.88310081.311528.82310091.351531.57110101.391536.647
10111.431539.96810121.531545.321 10131.71546.33710141.881546.58710150.951549.059
#Mann= 3 , 0 , 0
9849.033    0.04       09849.033    0.04       010150.95    0.04       0
#XS Ineff= 2 , 0
       0                               0
Bank Sta=9849.033,10150.95
Exp/Cntr=0.3,0.1

Type RM Length L Ch R = 1 ,23965.53,144.847200,144.847200,144.847200
XS GIS Cut Line= 6
750091.612758064752613.546454532750138.867442707752705.924222636
750156.490027359752748.633728243 750157.15640918 752750.51944701
750170.140120297752781.362905465750227.138678162752882.965617682
#Sta/Elev= 30
9849.0351575.4939856.4731570.5999873.1331560.3239878.4311556.5769884.3651552.747
9895.5971547.164 9906.831540.2229922.3471530.0089940.5271516.9389944.3051514.413
9952.7981510.4439968.876 1499.929973.4331497.2069984.2511491.8589995.0691489.549
10005.861490.11210016.711495.96110021.221499.49410027.561503.56210034.461505.059
10038.641505.76110064.841508.11810073.031510.06610085.281513.62710095.971515.927
10107.431516.606 10118.91518.52810130.361525.84310141.831531.91410150.961536.252
#Mann= 3 , 0 , 0
9849.035    0.04       09849.035    0.04       010150.96    0.04       0
#XS Ineff= 2 , 0
       0                               0
Bank Sta=9849.035,10150.96
Exp/Cntr=0.3,0.1

Type RM Length L Ch R = 1 ,23820.68,144.847300,144.847300,144.847300
XS GIS Cut Line= 6
749926.461214244752770.588521655750014.539603547752830.027393337
750075.777175178752849.256636213750102.690951781752862.703465678
750140.874398481752889.236091147 750181.99965995752924.872854304
#Sta/Elev= 30
9849.0871557.7269859.6751551.0989872.0761544.5319884.4761537.5559896.8761531.788
9920.9661519.1129926.3311516.8919944.3151508.432 9945.711507.9159955.9521502.702
9966.8091496.7459977.665 1489.039988.2411483.3819998.5031480.78910002.17 1481.16
10008.771482.37110019.071488.50210030.181494.03110041.361498.30310049.961500.918
10052.771501.57910064.951503.44710071.511504.623 10089.31508.38510115.141515.282
10120.531516.77110128.381519.245 10135.81522.41410141.611525.16910150.871528.406
#Mann= 3 , 0 , 0
9849.087  0.0422       09849.087  0.0422       010150.87  0.0422       0
#XS Ineff= 2 , 0
       0                               0
Bank Sta=9849.087,10150.87
Exp/Cntr=0.3,0.1

Type RM Length L Ch R = 1 ,23675.83,144.847200,144.847200,144.847200
XS GIS Cut Line= 5
749861.245506351752896.565819787749964.129518375752957.467316331
749990.841947121752972.044742811749992.630801505752972.939169997
750123.220236946753046.705415079
#Sta/Elev= 30
9849.011 1564.049853.3741560.9689864.9941551.9669876.6151546.2399899.8561536.349
9911.4771531.1739923.0981524.3249934.7181514.4079944.0941505.1959946.3391503.241
9963.7251492.0469969.5611488.8559984.2941482.2579992.3451477.681    99991476.631
   100011476.61410005.191476.99610015.211480.18210025.52 1484.9510026.691485.313
10038.18 1490.8110045.85 1492.0710061.15 1493.3610072.631495.47410084.121498.315
10106.85 1505.0110118.571507.98610127.181511.73810130.061512.77110150.981518.499
#Mann= 3 , 0 , 0
9849.011    0.04       09849.011    0.04       010150.98    0.04       0
#XS Ineff= 2 , 0
       0                               0
Bank Sta=9849.011,10150.98
Exp/Cntr=0.3,0.1

Type RM Length L Ch R = 1 ,23530.99,144.847300,144.847300,144.847300
XS GIS Cut Line= 6
749795.681391448753040.712910296749844.541418306753068.003492325
749884.916585364753087.837523172749911.322956603 753097.81400713
749984.800085182 753119.76146567750072.301506104  753159.3101471
#Sta/Elev= 30
 9849.031535.1389859.7041528.2339871.1581521.4739882.6121514.2669904.995 1503.68
9916.6471498.9639920.8631496.7579927.7891493.666 9938.931489.4539950.0681486.071
9960.7581481.8659971.4481478.6729978.2071476.1399982.0231474.9349992.4021472.231
    99991471.93210002.761471.89110013.121476.30710023.471478.62710026.161478.889
10033.991479.98910044.571481.25710055.151484.986   100661489.83910087.691495.935
10098.581499.11310109.661501.25410131.81 1506.3310142.891508.21510150.98 1510.67
#Mann= 3 , 0 , 0
 9849.03  0.0545       0 9849.03  0.0545       010150.98  0.0545       0
#XS Ineff= 2 , 0
       0                               0
Bank Sta=9849.03,10150.98
Exp/Cntr=0.3,0.1

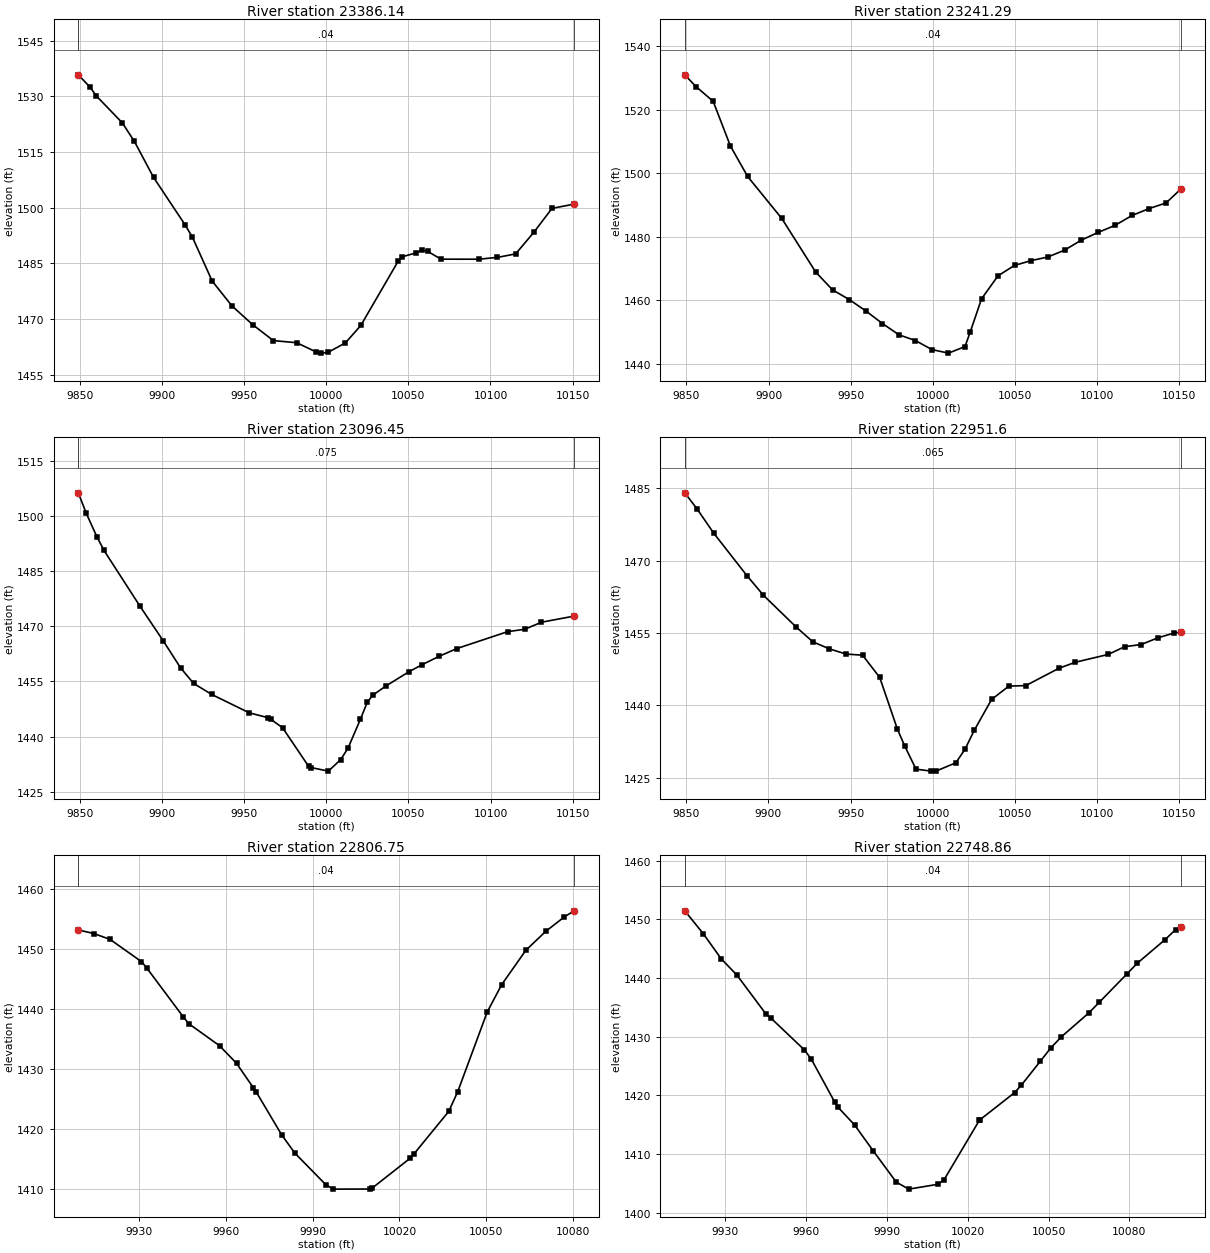
Type RM Length L Ch R = 1 ,23386.14,144.847200,144.847200,144.847200
XS GIS Cut Line= 6
749725.656225648753131.294791081749807.469782452753182.431758173
749867.112918822 753233.10177712749892.123683598753251.505398665
749928.050666842753272.478684417749977.168220416753295.936843935
#Sta/Elev= 30
9849.027 1535.789856.2751532.3999859.8991530.1399875.836 1522.84 9883.171517.843
9894.8051508.1899914.1771495.2969918.5111492.041 9930.541480.2519942.569 1473.57
9955.0891468.5559967.7691464.228 9982.061463.653 9994.041461.1149996.8481460.854
   100011461.04410011.681463.62310021.031468.29810043.941485.72910046.071486.774
10054.911487.87110058.251488.66210061.851488.23110069.821486.14810092.981486.141
10104.221486.629 10115.31487.56310126.381493.37610137.461499.82810150.95 1500.97
#Mann= 3 , 0 , 0
9849.027    0.04       09849.027    0.04       010150.95    0.04       0
#XS Ineff= 2 , 0
       0                               0
Bank Sta=9849.027,10150.95
Exp/Cntr=0.3,0.1

Type RM Length L Ch R = 1 ,23241.29,144.847300,144.847300,144.847300
XS GIS Cut Line= 6
 749668.56673177753319.853477769749714.733436828753334.695159764
749755.935828874753344.826472384749875.408294943 753359.09622025
749920.221812485753368.403295245749963.551987247  753380.1005502
#Sta/Elev= 30
9849.0281530.9079855.7861527.228 9866.291522.5929876.7941508.5459887.2981498.944
9908.0941485.739 9928.691468.9339938.988  1463.39949.133 1460.279959.2631456.675
9969.3921452.7189979.4521449.1669989.4961447.359 9999.541444.517 10009.61443.413
10019.661445.47810022.851450.07510029.721460.47610039.781467.73210049.841470.999
 10059.91472.49110070.111473.63310080.321475.79910090.531478.95910100.751481.362
10111.031483.58810121.391486.68710131.751488.856 10142.11490.63610150.961494.938
#Mann= 3 , 0 , 0
9849.028    0.04       09849.028    0.04       010150.96    0.04       0
#XS Ineff= 2 , 0
       0                               0
Bank Sta=9849.028,10150.96
Exp/Cntr=0.3,0.1

Type RM Length L Ch R = 1 ,23096.45,144.847200,144.847200,144.847200
XS GIS Cut Line= 6
749640.562955488753420.707568156749723.186153008753457.221911095
749791.289607045753501.532602765749814.998620211753514.000085912
749856.679440804753528.477897703749914.352882123753542.186272432
#Sta/Elev= 30
9849.0291506.3539853.8271500.8069860.2971494.4239864.6431490.677 9886.551475.495
9900.6941466.0739911.2991458.6889919.2031454.4619930.3081451.4399953.104 1446.45
9964.705  1445.19966.3131444.6649973.4051442.3739989.2291431.8929990.548 1431.56
10001.281430.573 10008.81433.73210013.221436.81210020.741444.65410024.93 1449.29
10028.191451.20610036.231453.73810050.571457.69810058.111459.506 10068.71461.836
10079.291463.91710110.481468.55710120.761469.19610131.041471.11910150.931472.786
#Mann= 3 , 0 , 0
9849.029   0.075       09849.029   0.075       010150.93   0.075       0
#XS Ineff= 2 , 0
       0                               0
Bank Sta=9849.029,10150.93
Exp/Cntr=0.3,0.1

Type RM Length L Ch R = 1 , 22951.6,144.847300,144.847300,144.847300
XS GIS Cut Line= 6
 749597.63603532753629.102146081749687.646940826753636.683597339
749720.838800906753629.019336418749759.880393658753604.912157848
749788.389058582753595.406906691749888.942845505753595.997554878
#Sta/Elev= 30
9849.1331484.0969856.5751480.7669866.6811475.7579886.8931466.9399896.9991462.848
 9917.07 1456.21 9927.071453.197 9937.071451.7429947.1721450.6649957.3091450.426
9967.7461445.8089978.5061435.0759982.9241431.6189989.8021426.798    99991426.384
10002.181426.41810014.061428.115 10019.71430.96110025.261434.844 10035.8 1441.24
10046.341444.02410056.581444.11710076.721447.69910086.731448.96310106.761450.581
10116.79 1452.1910126.821452.63610136.851454.01110146.871455.03210150.831455.188
#Mann= 3 , 0 , 0
9849.133   0.065       09849.133   0.065       010150.83   0.065       0
#XS Ineff= 2 , 0
       0                               0
Bank Sta=9849.133,10150.83
Exp/Cntr=0.3,0.1

Type RM Length L Ch R = 1 ,22806.75,57.890700,57.890700,57.890700
XS GIS Cut Line= 3
749666.331370709753691.738968413749714.248037338753728.544523973
749797.581370681753801.461190644
#Sta/Elev= 27
9909.1551453.2289914.5081452.6239920.0851451.6549930.9241447.9469932.6951446.933
9945.3041438.765 9947.341437.5629957.914  1433.99963.7561430.9719969.5751426.891
9970.5741426.1779979.3781419.0099983.8621416.0069994.5641410.718 9997.151409.973
10009.751409.98910010.441410.09110023.73 1415.1410024.941415.80410037.011422.939
10040.121426.237 10050.31439.53310055.311444.10910063.591449.80710070.491452.986
10076.881455.38910080.311456.417
#Mann= 3 , 0 , 0
9909.155    0.04       09909.155    0.04       010080.31    0.04       0
#XS Ineff= 2 , 0
       0                               0
Bank Sta=9909.155,10080.31
Exp/Cntr=0.3,0.1

Type RM Length L Ch R = 1 ,22748.86,42.443200,42.443200,42.443200
XS GIS Cut Line= 4
749629.525815129753736.877857313749673.970259577753770.211190641
 749732.30359292753819.516746208749769.109148443 753856.32230176
#Sta/Elev= 30
9915.012 1451.479921.8551447.5789928.5491443.2749934.3551440.5089945.2161433.819
9946.8551433.2279959.3551427.7689961.883 1426.249970.568 1418.929971.9161417.955
9977.986 1414.97 9985.011410.4899993.4771405.2159998.1041404.01410008.97 1404.84
 10011.2  1405.610024.291415.72310024.461415.81510037.381420.46410039.951421.777
10046.95 1425.8210050.761428.057 10054.71429.966 10064.91434.04710068.841435.885
10079.041440.69410082.99 1442.5710093.191446.54210097.131448.268   10099 1448.79
#Mann= 3 , 0 , 0
9915.012    0.04       09915.012    0.04       0   10099    0.04       0
#XS Ineff= 2 , 0
       0                               0
Bank Sta=9915.012,10099
Exp/Cntr=0.3,0.1

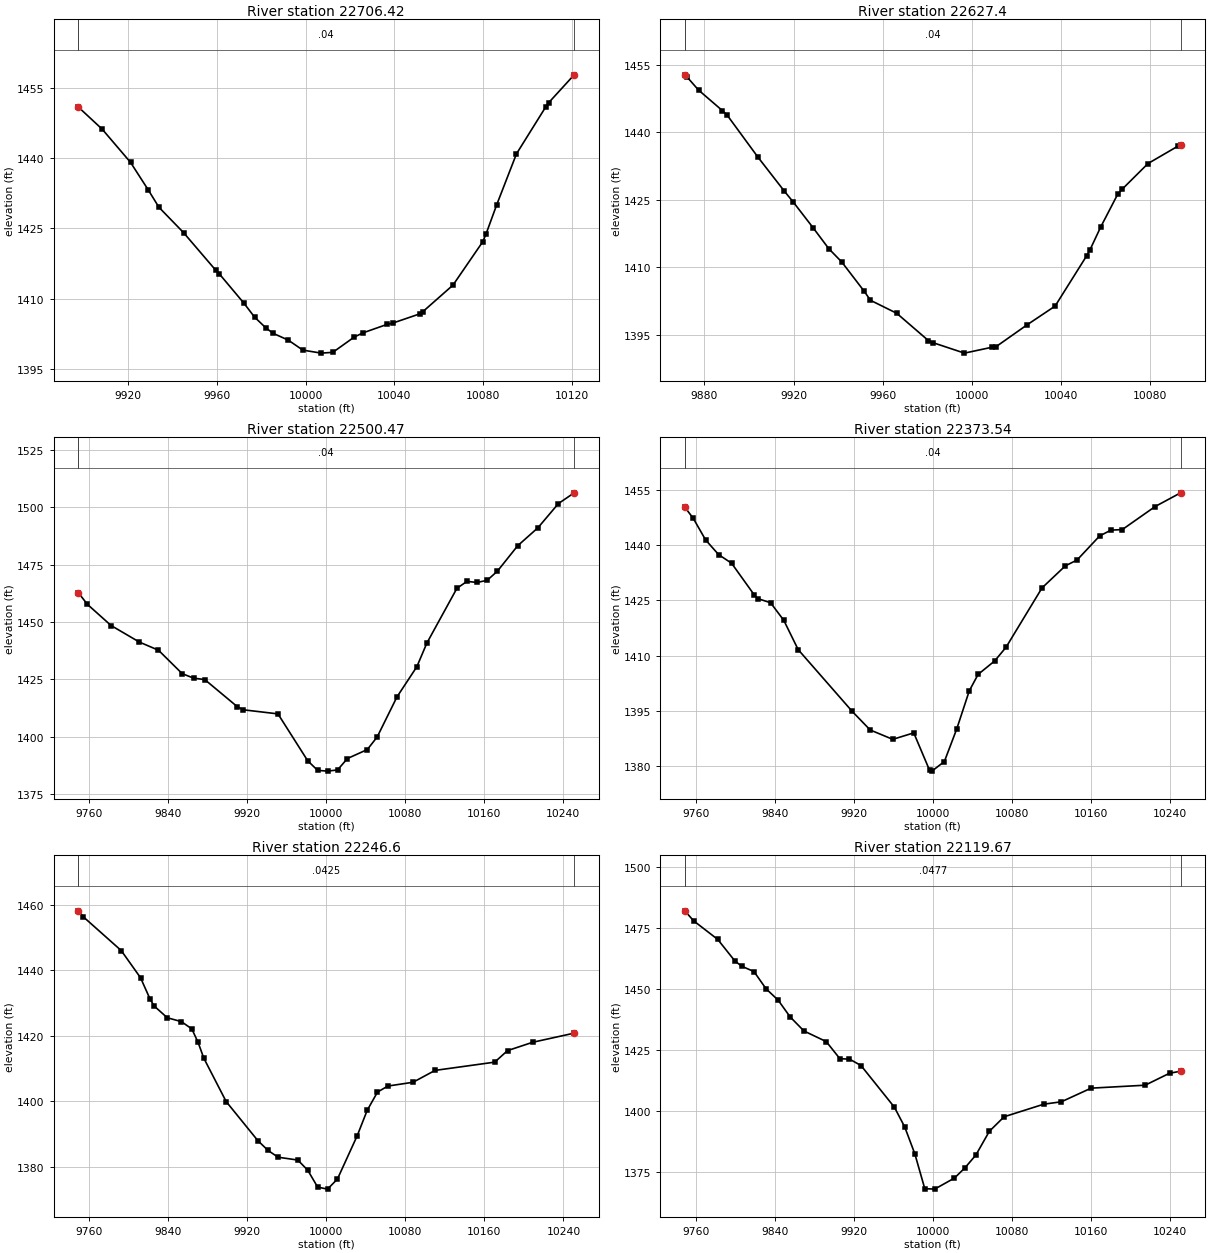
Type RM Length L Ch R = 1 ,22706.42,79.017700,79.017700,79.017700
XS GIS Cut Line= 4
749606.609148473753765.350079522749672.581370682753818.127857298
749749.664703995753888.266746208749772.581370711753914.655635089
#Sta/Elev= 30
9897.4581450.9249908.2041446.208 9921.011439.1089928.9131433.2969933.8161429.525
9944.9211424.1089959.4291416.0889960.9291415.3749972.2351408.9999976.937 1406.08
9981.9441403.8199985.2141402.6369992.155 1401.169998.7341399.02710007.011398.384
10012.251398.55210021.871401.80110025.771402.69810036.731404.52310039.291404.797
10051.591406.78610052.811407.21510066.451412.90610079.851422.14410081.311423.753
10086.161430.03910095.081440.92610108.321450.97610109.551451.81810121.111457.804
#Mann= 3 , 0 , 0
9897.458    0.04       09897.458    0.04       010121.11    0.04       0
#XS Ineff= 2 , 0
       0                               0
Bank Sta=9897.458,10121.11
Exp/Cntr=0.3,0.1

Type RM Length L Ch R = 1 , 22627.4,126.932200,126.932200,126.932200
XS GIS Cut Line= 4
749580.220259547753824.377857313749645.498037338753877.155635089
749718.414703995753949.377857327749742.720259577753975.766746208
#Sta/Elev= 29
9871.2061452.7789872.1961452.3039877.3531449.3969888.101 1444.819890.2121443.815
9904.0061434.4859915.9311426.8799919.9111424.4689928.7911418.7669935.8171414.126
 9941.65 1411.169951.7221404.649 9954.511402.6569966.2981399.7689980.5081393.696
9982.599 1393.239996.6741390.91310008.931392.21110010.751392.31210024.821397.218
10037.35 1401.3710051.561412.59310052.971413.85310057.781418.92710065.421426.225
 10067.51427.38410079.021433.05610092.611436.97310093.661437.187
#Mann= 3 , 0 , 0
9871.206    0.04       09871.206    0.04       010093.66    0.04       0
#XS Ineff= 2 , 0
       0                               0
Bank Sta=9871.206,10093.66
Exp/Cntr=0.3,0.1

Type RM Length L Ch R = 1 ,22500.47,126.932200,126.932200,126.932200
XS GIS Cut Line= 6
749427.397837672753940.840786587749519.128043939 754001.67210927
  749581.4190957754028.665438911 749619.34944976754033.161472138
749730.780817753754027.315074193749900.501734808754062.787022561
#Sta/Elev= 30
9749.1311462.7939758.2531457.7189782.2511448.4679810.938 1441.239830.2471437.683
9854.245 1427.469865.8121425.5029877.0751424.8799909.8621413.1069916.1581411.688
9951.1611409.9129981.263 1389.469991.3131385.26910001.371384.93610011.441385.449
 10021.51390.43810041.591394.35210051.591399.84410071.611417.31510091.741430.499
10101.831440.77610132.291464.70610142.471467.71410152.651467.24410162.921468.189
10173.211472.152 10193.81483.26910214.381491.15810234.97 1501.6510250.93 1506.35
#Mann= 3 , 0 , 0
9749.131    0.04       09749.131    0.04       010250.93    0.04       0
#XS Ineff= 2 , 0
       0                               0
Bank Sta=9749.131,10250.93
Exp/Cntr=0.3,0.1

Type RM Length L Ch R = 1 ,22373.54,126.932200,126.932200,126.932200
XS GIS Cut Line= 6
749438.977719589753979.420880248749503.958458533754034.839639617
 749607.03798327754132.063502977749667.167351296754178.894286126
749743.586135035754230.332310001749838.168719641754279.135682772
#Sta/Elev= 30
9749.028  1450.39757.626 1447.269770.0861441.4229783.2291437.4419796.3721435.099
9819.2681426.5329822.6581425.5269835.8631424.3739849.2391419.6089863.8141411.655
9918.3411394.9569936.6851389.867 9959.581387.3189980.8141389.0789996.773 1378.96
9999.1771378.69910011.811381.30310024.411390.20210037.021400.47910045.951404.937
10062.851408.61910074.261412.31210110.681428.40710134.341434.39710146.121435.962
10169.011442.49910180.451444.07810191.891444.21510225.231450.48210250.981454.193
#Mann= 3 , 0 , 0
9749.028    0.04       09749.028    0.04       010250.98    0.04       0
#XS Ineff= 2 , 0
       0                               0
Bank Sta=9749.028,10250.98
Exp/Cntr=0.3,0.1

Type RM Length L Ch R = 1 , 22246.6,126.932200,126.932200,126.932200
XS GIS Cut Line= 6
749402.914057184753981.523563582749500.962559559754099.249425538
749515.293826426754235.114723065749532.072500857754278.064263681
749583.301272744 754339.74922029749650.113734629754388.151030501
#Sta/Elev= 30
9749.1411458.2369754.3221456.3659792.5621446.0889812.0691437.7919821.8011431.202
9825.778 1429.17 9839.131425.5589853.4191424.3749863.947 1422.159870.3091418.027
 9876.081413.2129898.7341399.9349930.7551388.0089940.9511385.0439951.1471382.943
9971.2291382.0649981.242 1378.979991.2571373.80610001.281373.18210011.28 1376.26
10031.341389.52710041.381397.24810051.811402.83510062.25 1404.6810087.78 1405.84
10110.041409.46910170.391411.98810183.38 1415.5110208.771418.055 10250.81420.854
#Mann= 3 , 0 , 0
9749.141  0.0425       09749.141  0.0425       0 10250.8  0.0425       0
#XS Ineff= 2 , 0
       0                               0
Bank Sta=9749.141,10250.8
Exp/Cntr=0.3,0.1

Type RM Length L Ch R = 1 ,22119.67,126.932200,126.932200,126.932200
XS GIS Cut Line= 6
749197.664586224754105.877751739749358.725730422754214.512972091
749439.152040172754228.893318036749456.622122454754237.121667698
 749542.44059198754329.147247296749604.078909237754378.957416663
#Sta/Elev= 30
9749.1091482.0239758.0621477.9279782.456 1470.319799.8961461.4429806.8871459.313
9819.0931457.1669831.2991450.1269843.505 1445.489855.7121438.5979869.6521432.851
9892.2171428.5029906.0311421.4889915.6541421.3579927.373 1418.719961.1461401.657
9971.5981393.5589981.835 1382.559991.8571368.33610001.881368.13310021.911372.668
10032.531376.85610043.581382.09110057.181391.79510072.151397.74810112.291402.897
10130.031403.87710160.141409.45510214.811410.66110239.511415.56310250.691416.386
#Mann= 3 , 0 , 0
9749.109  0.0477       09749.109  0.0477       010250.69  0.0477       0
#XS Ineff= 2 , 0
       0                               0
Bank Sta=9749.109,10250.69
Exp/Cntr=0.3,0.1

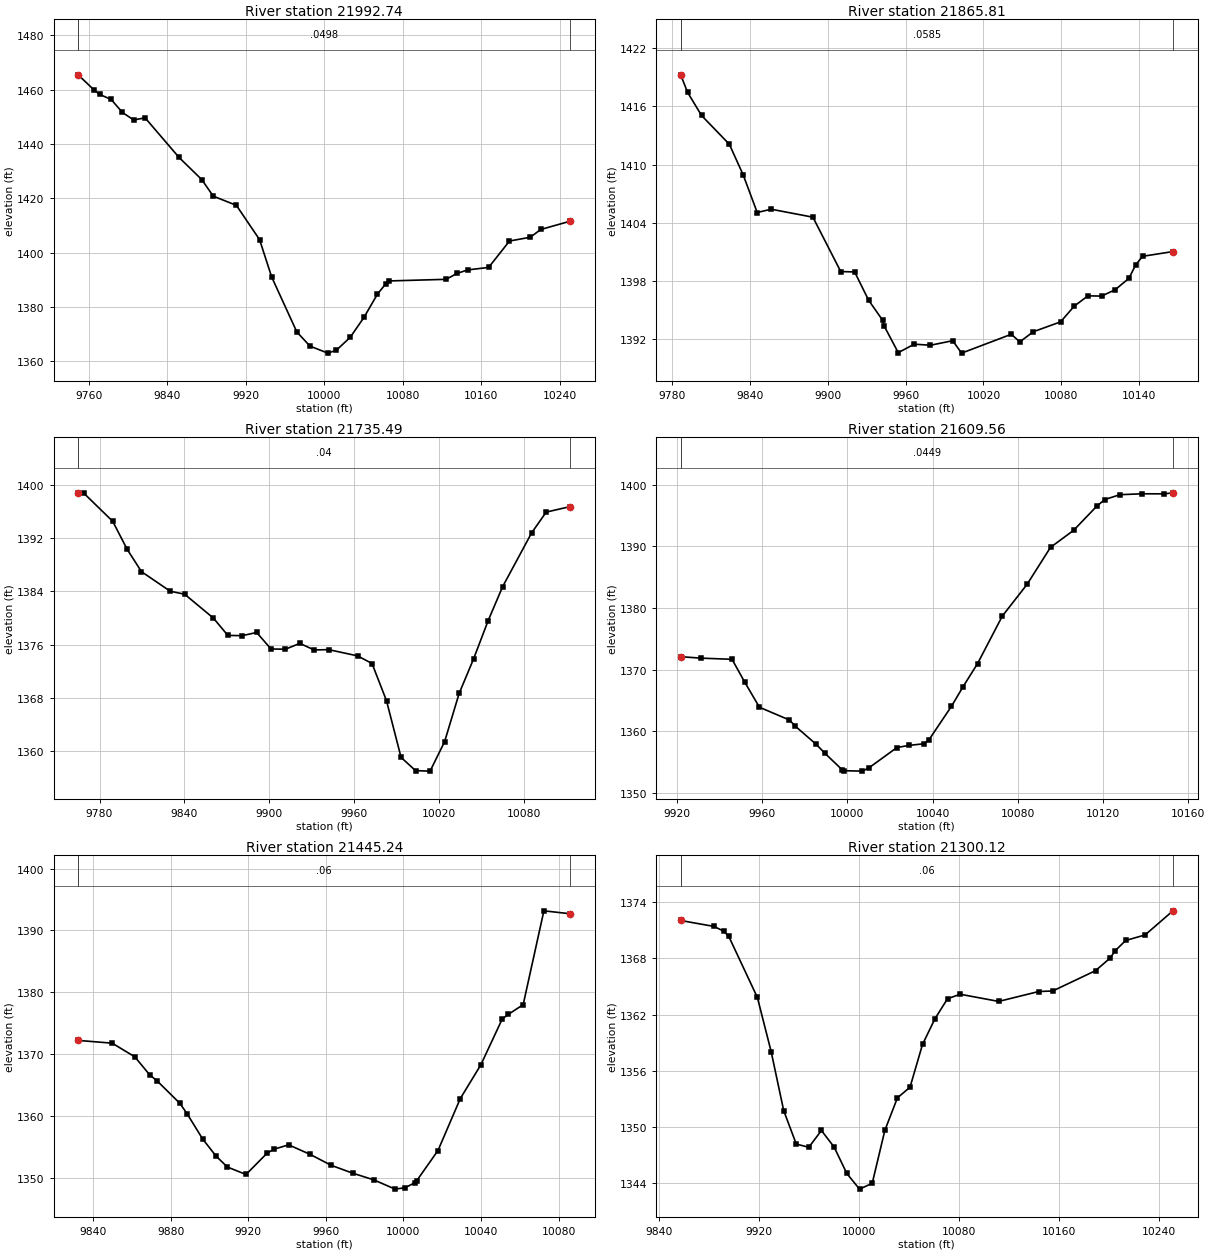
Type RM Length L Ch R = 1 ,21992.74,126.932200,126.932200,126.932200
XS GIS Cut Line= 6
749145.869624728754186.752073046749307.476909274754282.527767315
749391.742738476754357.722939438749422.561554291 754379.58942538
749483.014658179754408.394743245749573.471116063754440.798106681
#Sta/Elev= 30
9749.0291465.4539765.5481459.7789771.1091458.2249782.6511456.3879794.1931451.595
9805.6021448.8469817.2761449.6239851.9021435.0379874.9851426.9259886.7681420.802
9910.3791417.401 9933.991404.7979946.3391391.0359971.9611370.8349985.3221365.619
10003.531363.019 10012.31364.087 10026.41368.837 10040.51376.20910054.011384.638
10062.591388.52210066.271389.59110124.241390.18510135.151392.33310146.071393.638
10167.541394.56610188.791404.28110210.031405.67510220.661408.529 10250.91411.604
#Mann= 3 , 0 , 0
9749.029  0.0498       09749.029  0.0498       0 10250.9  0.0498       0
#XS Ineff= 2 , 0
       0                               0
Bank Sta=9749.029,10250.9
Exp/Cntr=0.3,0.1

Type RM Length L Ch R = 1 ,21865.81,130.316600,130.316600,130.316600
XS GIS Cut Line= 6
749130.038119644754347.615477309749276.334218413754404.230063498
749319.421425581754435.292933792749358.500520438754456.836537361
749370.023843318754458.840593487 749477.24084717754493.911576092
#Sta/Elev= 30
9786.8241419.2659792.1451417.4529802.8671415.0689824.3131412.0889834.9941408.916
9845.7581405.0419856.4811405.3829888.6491404.5589910.0941398.9419920.8171398.902
 9931.541395.9869942.2621393.9279943.6931393.2789954.3761390.5659966.7041391.439
9979.209 1391.339996.3091391.79910003.181390.51510041.431392.46210048.031391.678
10058.371392.72210079.411393.74610089.931395.36810100.451396.43410110.971396.407
10121.491397.06710132.021398.24210137.271399.63610142.541400.51610165.941401.006
#Mann= 3 , 0 , 0
9786.824  0.0585       09786.824  0.0585       010165.94  0.0585       0
#XS Ineff= 2 , 0
       0                               0
Bank Sta=9786.824,10165.94
Exp/Cntr=0.3,0.1

Type RM Length L Ch R = 1 ,21735.49,125.934100,125.934100,125.934100
XS GIS Cut Line= 3
749110.999586195754519.964306027749295.372751802754555.035288587
 749451.68913132754591.108299255
#Sta/Elev= 30
9764.8871398.794 9768.961398.7259789.3181394.5189799.497 1390.339809.6771386.958
9830.0351384.0219840.2151383.5749860.573 1379.989870.7531377.3919880.9321377.355
9891.1111377.835 9901.291375.353 9911.471375.3229921.6491376.1959931.8281375.208
9942.0081375.2589962.4471374.323 9972.711373.1769982.9721367.5679993.2351359.086
 10003.51357.09310013.761357.02210024.02 1361.4410034.291368.67610044.551373.885
10054.811379.60610065.071384.712 10085.61392.79510095.861395.89910112.991396.736
#Mann= 3 , 0 , 0
9764.887    0.04       09764.887    0.04       010112.99    0.04       0
#XS Ineff= 2 , 0
       0                               0
Bank Sta=9764.887,10112.99
Exp/Cntr=0.3,0.1

Type RM Length L Ch R = 1 ,21609.56,164.311200,164.311200,164.311200
XS GIS Cut Line= 6
 749323.26270737754732.697943392749350.152994714 754719.78269271
749399.314887593754660.934893295749420.341638374754644.155978579
  749446.4336936754628.617681041749508.830848066754605.129137695
#Sta/Elev= 30
9921.7351372.086 9931.231371.8489945.8391371.661 9951.851367.9199958.7031363.874
9972.7621361.8029975.592 1360.789985.4051357.8359989.4971356.3779997.6291353.689
9998.3731353.56310007.061353.49610010.111354.03110023.271357.32910028.771357.667
10036.051357.94910038.291358.58510048.841364.01710054.321367.22510061.091370.954
10072.731378.68310084.371383.84410095.351389.84310106.211392.61210117.081396.536
10120.881397.61810127.94  1398.410138.461398.54710148.851398.53510152.831398.702
#Mann= 3 , 0 , 0
9921.735  0.0449       09921.735  0.0449       010152.83  0.0449       0
#XS Ineff= 2 , 0
       0                               0
Bank Sta=9921.735,10152.83
Exp/Cntr=0.3,0.1

Type RM Length L Ch R = 1 ,21445.24,145.122700,145.122700,145.122700
XS GIS Cut Line= 6
 749299.93317467754736.094586805749360.954631895754772.591802403
749447.947185725 754812.08868809749449.745165497754812.964626938
749497.812429488754835.506297067749527.797757953754846.771670133
#Sta/Elev= 30
9832.358  1372.29849.9141371.7539861.5661369.5459869.1891366.6469873.2181365.604
 9884.871361.9949888.6711360.2589896.5231356.2569903.4611353.4749909.2861351.712
9918.8861350.5049929.8691353.9879933.475 1354.619940.8511355.3039951.8341353.774
9962.8161351.9889973.7981350.7279984.7811349.6339995.7631348.135   100011348.374
10005.791349.156 10006.81349.45310017.851354.38310029.351362.78410039.941368.245
10050.98 1375.6710054.091376.40910061.771377.98210072.45 1393.1710086.121392.692
#Mann= 3 , 0 , 0
9832.358    0.06       09832.358    0.06       010086.12    0.06       0
#XS Ineff= 2 , 0
       0                               0
Bank Sta=9832.358,10086.12
Exp/Cntr=0.3,0.1

Type RM Length L Ch R = 1 ,21300.12,145.122600,145.122600,145.122600
XS GIS Cut Line= 6
749271.721369147754748.030350685749332.571947426754782.714398742
749321.075208426754895.245964572749326.550168604754955.043986261
749353.507092297755021.094554394749398.437437713755085.122555494
#Sta/Elev= 30
9857.2131372.0319884.0081371.3959891.4821370.8939895.5181370.3779918.5391363.827
9929.5491358.057 9939.591351.7659949.6271348.2029959.6591347.8549969.7461349.646
9979.9081347.8839990.0711345.06210000.241343.39610010.391344.01910020.491349.665
10030.541353.131 10040.61354.258 10050.6 1358.82 10060.61361.57410070.611363.691
10080.741364.169 10111.51363.40510143.591364.462 10154.71364.51710188.971366.685
10200.771368.04310204.641368.80410213.07  1369.910228.611370.49310250.861373.062
#Mann= 3 , 0 , 0
9857.213    0.06       09857.213    0.06       010250.86    0.06       0
#XS Ineff= 2 , 0
       0                               0
Bank Sta=9857.213,10250.86
Exp/Cntr=0.3,0.1