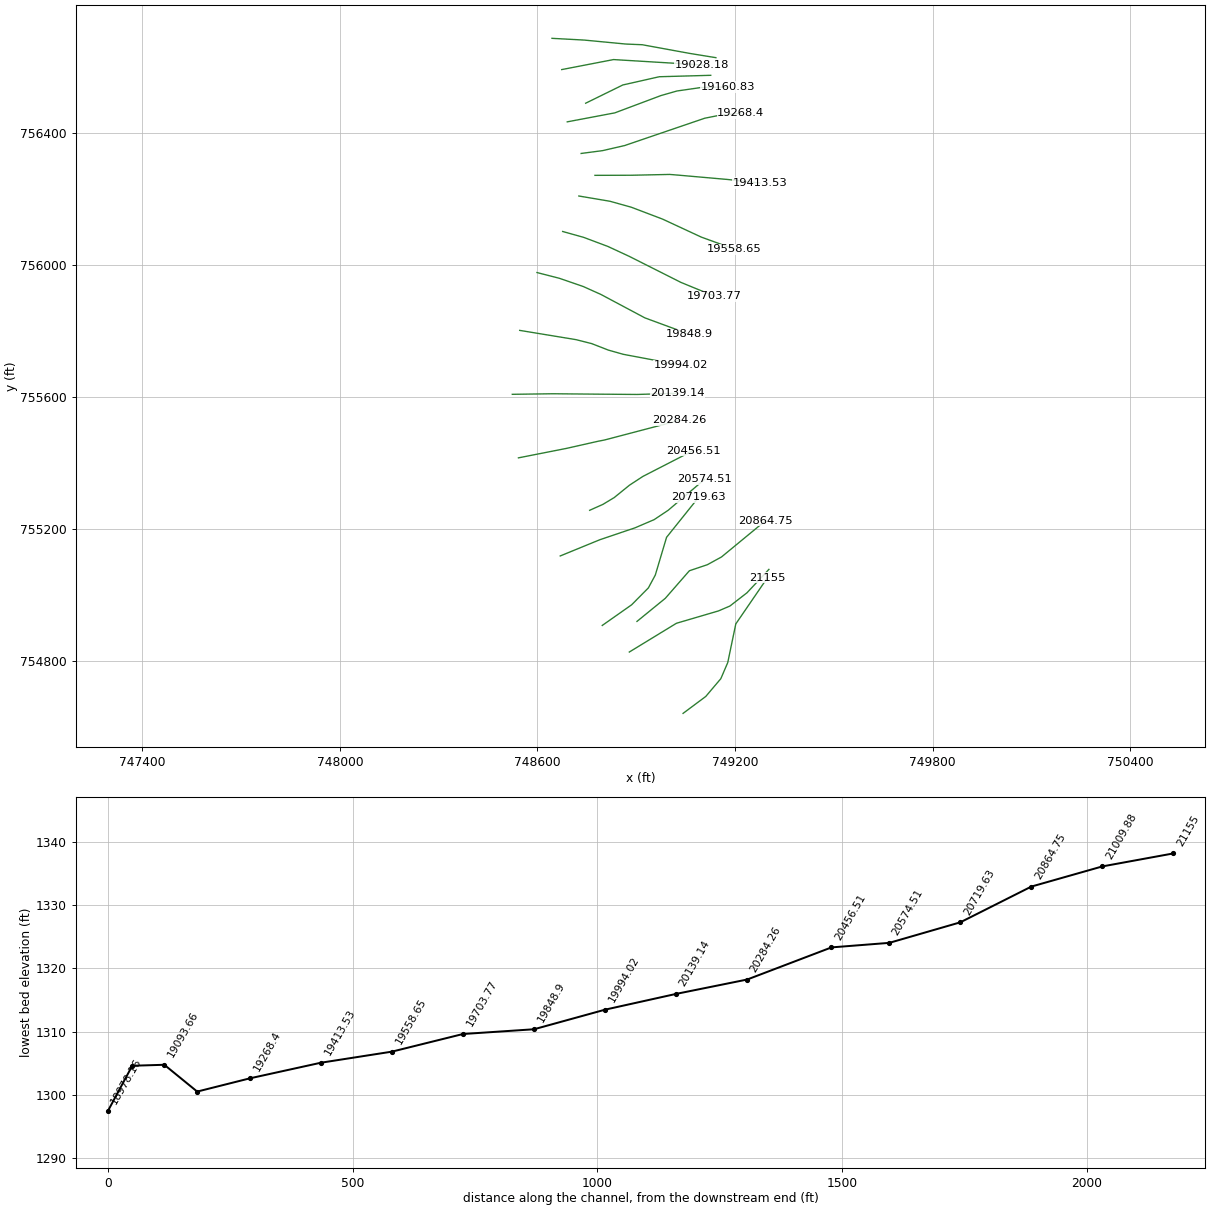
HEC-RAS study 14313_ras.prj: 14313

--- 14313_ras.g01 (geometry) --- (continued)

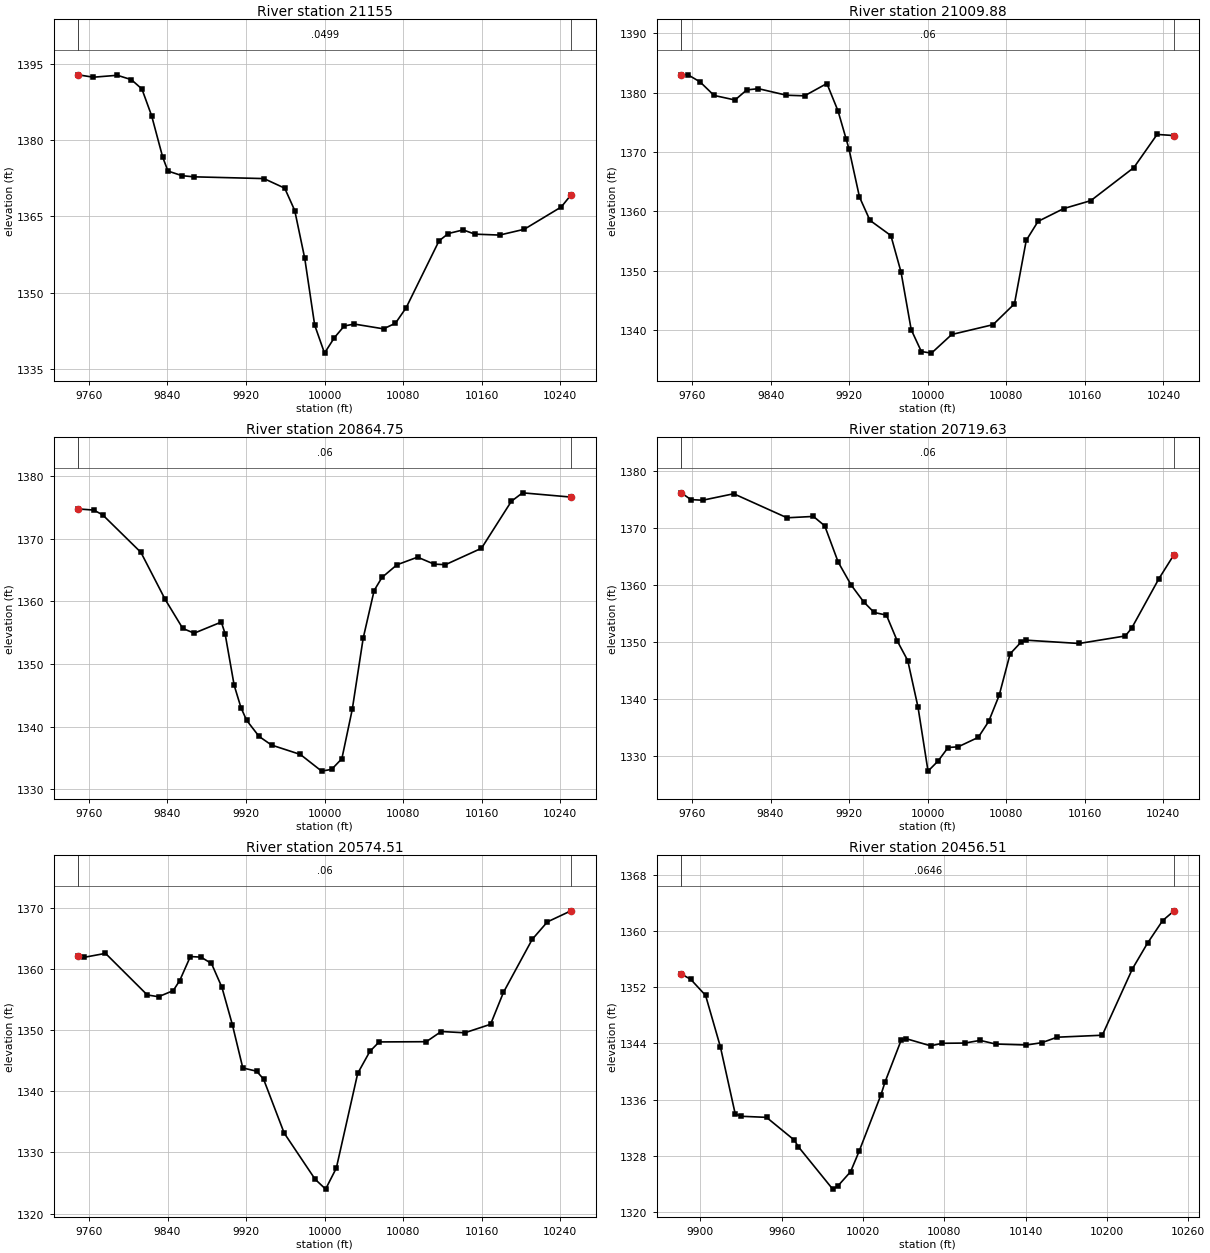
Type RM Length L Ch R = 1 ,   21155,145.122700,145.122700,145.122700
XS GIS Cut Line= 6
749042.320652475754640.824338335749111.272986288754692.152243242
749157.005594903754746.085151679749178.034312388754795.012815386
749202.429213417754912.158964413749298.968926101755052.872836288
#Sta/Elev= 30
9749.1441392.8129764.6071392.3449788.9971392.7219803.2721391.8659814.042 1390.03
9823.9591384.7579835.1721376.6579840.5371373.9139854.9311372.9989866.9361372.777
9938.3061372.4299959.4451370.5499969.6521366.1579979.8581356.745 9989.951343.652
9999.9751338.14310009.981341.16910020.051343.47210030.161343.85610060.081342.913
10072.22 1344.0210083.161347.08310116.571360.19510126.061361.63910141.151362.349
10153.121361.51410178.241361.33410203.351362.47110241.031366.85310250.921369.212
#Mann= 3 , 0 , 0
9749.144  0.0499       09749.144  0.0499       010250.92  0.0499       0
#XS Ineff= 2 , 0
       0                               0
Bank Sta=9749.144,10250.92
Exp/Cntr=0.3,0.1

Type RM Length L Ch R = 1 ,21009.88,145.122600,145.122600,145.122600
XS GIS Cut Line= 6
748879.035061817754826.900354348749022.225237382754914.174486079
749149.822105516754951.610776223749184.552724063754966.442712285
749236.573083976 755006.75189874749302.988511263755077.619077895
#Sta/Elev= 30
9749.0791382.9979756.1791382.9719768.0831381.8179782.4461379.5249803.7931378.754
9815.6971380.452  9827.61380.6639856.1861379.5589874.5941379.4599897.3161381.532
9908.6761376.9069916.8851372.2089919.8431370.4889930.5051362.4049941.1671358.471
9962.4911355.9039972.8331349.748 9983.17 1340.059993.5081336.35710003.831336.091
10024.451339.23210066.531340.88810088.331344.40710100.33  1355.110112.341358.296
 10138.4 1360.4510166.061361.79210209.931367.36710233.571372.95110250.861372.761
#Mann= 3 , 0 , 0
9749.079    0.06       09749.079    0.06       010250.86    0.06       0
#XS Ineff= 2 , 0
       0                               0
Bank Sta=9749.079,10250.86
Exp/Cntr=0.3,0.1

Type RM Length L Ch R = 1 ,20864.75,145.122700,145.122700,145.122700
XS GIS Cut Line= 6
748902.364165998 754919.78525744748988.417847134754989.881785064
749061.484132041755073.449675233749116.009857723755091.774254667
749159.134770224755115.371655411749292.156858928755224.825072612
#Sta/Elev= 30
9749.1681374.7669765.0961374.5799774.1591373.8139813.0431367.8299837.7251360.324
9855.6641355.6869867.2941354.9289894.9291356.706 9898.741354.8559907.9841346.621
9914.9091343.0469920.6681341.0219933.3531338.4449946.0371337.0679975.3971335.567
9997.0391332.90410007.231333.18510017.661334.89110028.261342.77510039.361354.125
10050.521361.74110058.491363.82510073.711365.84410094.751367.06610111.591365.952
10123.121365.86510159.831368.48610190.281375.99510201.661377.33710250.931376.657
#Mann= 3 , 0 , 0
9749.168    0.06       09749.168    0.06       010250.93    0.06       0
#XS Ineff= 2 , 0
       0                               0
Bank Sta=9749.168,10250.93
Exp/Cntr=0.3,0.1

Type RM Length L Ch R = 1 ,20719.63,145.122700,145.122700,145.122700
XS GIS Cut Line= 6
748796.887284735 754907.54149655748886.173491061754970.214055618
748936.964802789755021.472481577748957.941878094755060.244229698
748992.216153675755174.948501411749089.462251149755296.123504771
#Sta/Elev= 30
9749.1121376.1319758.8231374.9439770.7941374.8299802.4971375.9689856.7811371.748
9883.6471371.9859895.1661370.3359908.8781363.9629922.0341359.9519934.7371356.999
9945.4621355.1239958.0011354.6569968.9851350.1319979.7131346.6749990.1591338.495
10000.361327.25910010.581329.031 10020.81331.40810031.021331.52610051.53 1333.19
10062.171336.00210072.811340.57210083.961347.85910095.111349.91210100.321350.256
10154.131349.67510201.231350.99510207.711352.36110235.481361.05610250.921365.298
#Mann= 3 , 0 , 0
9749.112    0.06       09749.112    0.06       010250.92    0.06       0
#XS Ineff= 2 , 0
       0                               0
Bank Sta=9749.112,10250.92
Exp/Cntr=0.3,0.1

Type RM Length L Ch R = 1 ,20574.51,117.993600,117.993600,117.993600
XS GIS Cut Line= 6
748669.249410388755118.355710801748789.443285682755167.522161386
748896.326618219755203.630362476748954.430248637755228.489033804
748996.974073807755256.796850777749107.421709947755350.540818878
#Sta/Elev= 30
9749.0141362.1579755.2271361.8969776.8361362.5389819.3881355.7429830.8571355.455
9845.8011356.4469852.4661358.101 9863.271362.0199874.0741361.9249884.7851360.884
 9895.421356.9899906.0551350.891 9916.691343.8149930.7541343.2879937.805    1342
 9958.811333.1799990.3181325.63710001.031324.01510011.931327.44610033.731342.934
10046.15 1346.5310055.581348.06610103.621348.10410118.751349.76910142.831349.561
10169.06 1350.9510182.181356.16610211.471364.82810226.921367.68110250.941369.489
#Mann= 3 , 0 , 0
9749.014    0.06       09749.014    0.06       010250.94    0.06       0
#XS Ineff= 2 , 0
       0                               0
Bank Sta=9749.014,10250.94
Exp/Cntr=0.3,0.1

Type RM Length L Ch R = 1 ,20456.51,172.251700,172.251700,172.251700
XS GIS Cut Line= 6
748758.642023058755256.832921046 748798.71116158755274.724145019
748833.194276932 755295.43146393748879.860909023755333.234035546
748920.486327378 755359.70018482749072.595327241755437.822781361
#Sta/Elev= 30
9885.8371353.866  9892.8 1353.119903.752 1350.839914.7031343.5089925.6551333.969
9930.2551333.6499948.7191333.4989969.1041330.2879972.247 1329.329997.5791323.299
10001.281323.72210010.77 1325.7710017.031328.65710033.241336.71710036.141338.489
10048.071344.44510051.56 1344.6910069.881343.66210078.491344.02310095.021344.055
10106.421344.43310117.811343.91810140.59 1343.7810151.991344.11210163.151344.886
10196.551345.16910218.811354.61410229.941358.25910241.071361.45410249.531362.846
#Mann= 3 , 0 , 0
9885.837  0.0646       09885.837  0.0646       010249.53  0.0646       0
#XS Ineff= 2 , 0
       0                               0
Bank Sta=9885.837,10249.53
Exp/Cntr=0.3,0.1

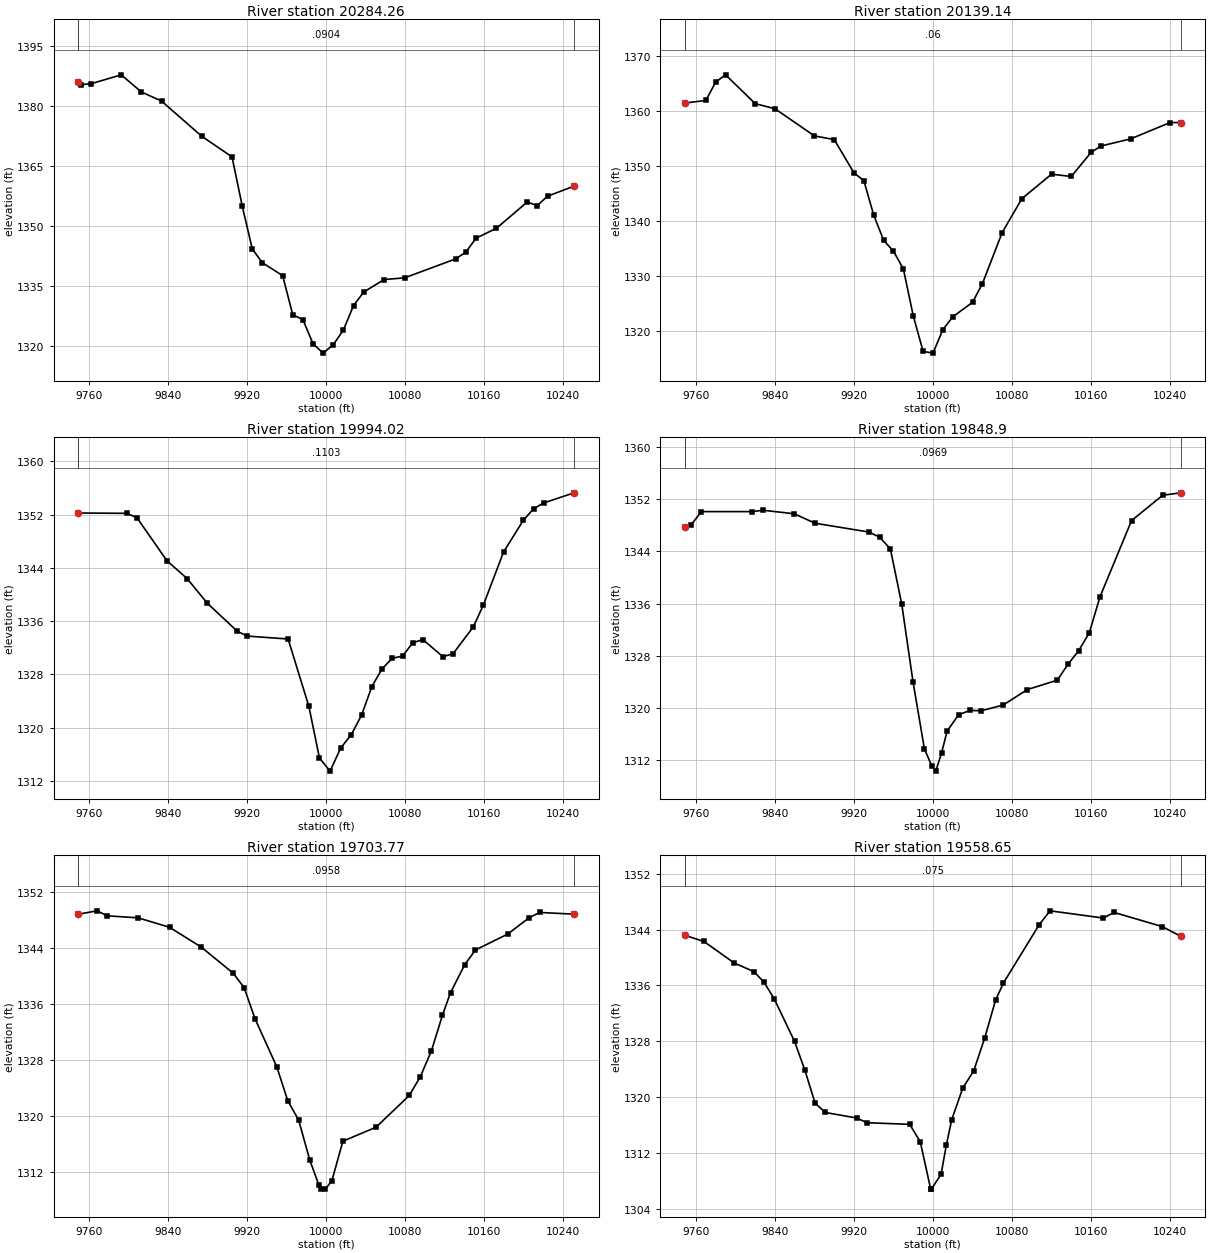
Type RM Length L Ch R = 1 ,20284.26,145.122600,145.122600,145.122600
XS GIS Cut Line= 6
748542.368448718755415.934304873  748689.0112308755444.793568357
748787.071228726755466.916512306 748789.04752638755467.223509998
748804.376694182755470.225558512749031.075537988755529.692250495
#Sta/Elev= 30
 9749.021385.8269751.7021385.2679761.8941385.4929792.4691387.7229812.8531383.435
9833.2361381.1759874.0041372.3699904.6151367.2319914.866 1355.059925.1171344.236
9935.3691340.7919955.8711337.5689966.123 1327.799976.3741326.6029986.6251320.572
9996.8771318.22410007.071320.33110017.261323.931 10027.61330.08810037.941333.478
10058.621336.60110079.291337.02310130.99 1341.7510141.321343.44110151.661346.932
10172.341349.40410203.351355.93810213.691355.08310224.031357.41110250.991359.932
#Mann= 3 , 0 , 0
 9749.02  0.0904       0 9749.02  0.0904       010250.99  0.0904       0
#XS Ineff= 2 , 0
       0                               0
Bank Sta=9749.02,10250.99
Exp/Cntr=0.3,0.1

Type RM Length L Ch R = 1 ,20139.14,145.122700,145.122700,145.122700
XS GIS Cut Line= 6
748523.735486496755608.680382159 748646.67632291755610.381120144
748773.713356178755609.245816318748775.713258156755609.226015308
748902.897527748 755608.24424298749025.640224535755611.904913301
#Sta/Elev= 30
9749.0051361.3939770.2721361.8599780.2731365.1889790.2741366.5169820.2771361.281
9840.2791360.3559880.2821355.4189900.2831354.7539920.2841348.6989930.2841347.298
9940.2841341.0169950.2851336.4669960.2851334.4719970.2851331.2529980.2861322.741
9990.2861316.27110000.291315.95510010.291320.23510020.291322.53910040.291325.188
10050.291328.56310070.291337.85510090.291344.01910120.291348.466 10140.31348.046
 10160.31352.42310170.311353.57910200.321354.87510240.341357.84510250.991357.848
#Mann= 3 , 0 , 0
9749.005    0.06       09749.005    0.06       010250.99    0.06       0
#XS Ineff= 2 , 0
       0                               0
Bank Sta=9749.005,10250.99
Exp/Cntr=0.3,0.1

Type RM Length L Ch R = 1 ,19994.02,145.122700,145.122700,145.122700
XS GIS Cut Line= 6
748546.172076327755802.626973892748716.931422748755774.577758732
 748764.63225068755762.549291552748815.734950955755742.733643793
748860.597696992755730.064142323749035.648586673755697.137635925
#Sta/Elev= 30
 9749.051352.2479798.3711352.1999808.4711351.5219838.7741345.0669859.1021342.404
 9879.461338.7179909.9991334.4739920.1781333.7559961.4051333.3159982.4171323.194
9993.1031315.43810003.861313.46410014.611316.92910025.361318.94610035.781321.884
10046.171326.17310056.561328.85210066.951330.42510077.271330.754 10087.5 1332.74
10097.721333.23310118.171330.65410128.39 1331.1110148.841335.12910159.07 1338.42
10179.431346.37310199.67 1351.19 10209.81352.86910219.921353.75710250.95 1355.28
#Mann= 3 , 0 , 0
 9749.05  0.1103       0 9749.05  0.1103       010250.95  0.1103       0
#XS Ineff= 2 , 0
       0                               0
Bank Sta=9749.05,10250.95
Exp/Cntr=0.3,0.1

Type RM Length L Ch R = 1 , 19848.9,145.122600,145.122600,145.122600
XS GIS Cut Line= 6
748598.685444037755978.051733455 748666.29340731755960.744881779
748739.266494062755935.667673072748792.785819656755911.653596196
748926.384889587755840.568932592 749062.24760879755790.571022844
#Sta/Elev= 30
 9749.071347.7019755.5881348.0599765.9111350.0589817.5231350.0599828.0641350.269
9859.7861349.7329880.934 1348.289935.1861346.9429946.5051346.1349957.2181344.323
9968.6831335.8929980.1481323.9589991.6131313.769    99991311.19510003.11 1310.37
10008.941313.14210014.661316.52110026.211318.98610037.761319.65810049.011319.596
10071.23 1320.4710095.931322.84910126.171324.28310136.95 1326.7110147.741328.786
10158.511331.514 10169.31337.01810201.281348.68210232.821352.56310250.951352.931
#Mann= 3 , 0 , 0
 9749.07  0.0969       0 9749.07  0.0969       010250.95  0.0969       0
#XS Ineff= 2 , 0
       0                               0
Bank Sta=9749.07,10250.95
Exp/Cntr=0.3,0.1

Type RM Length L Ch R = 1 ,19703.77,145.122700,145.122700,145.122700
XS GIS Cut Line= 6
748676.718581869   756102.598283748740.393404847756084.813072136
748814.133778397756057.178686267748879.091504043756027.074977118
749035.755141994755948.215065003749137.552271612755906.412692022
#Sta/Elev= 30
9749.0531348.7799768.034 1349.269778.4161348.5499809.5651348.2629841.4421346.911
 9873.481344.0959905.8891340.3699916.9111338.3139927.9331333.8779949.9761327.033
9960.9981322.2369972.1121319.4359983.2921313.7929992.5181310.1989994.4711309.628
    9999 1309.6210005.661310.79510016.861316.44510050.461318.44610084.061322.957
10095.261325.63610106.461329.30410117.661334.39910125.831337.60410140.051341.546
10150.981343.679 10183.71345.94610205.511348.293 10216.21349.02810250.981348.783
#Mann= 3 , 0 , 0
9749.053  0.0958       09749.053  0.0958       010250.98  0.0958       0
#XS Ineff= 2 , 0
       0                               0
Bank Sta=9749.053,10250.98
Exp/Cntr=0.3,0.1

Type RM Length L Ch R = 1 ,19558.65,145.122600,145.122600,145.122600
XS GIS Cut Line= 6
748725.780017208756210.249243982748820.508784837756194.261468938
748885.032019255  756176.2440212748980.120227175756140.153183147
 749097.39380282756085.699210751749198.658569945756048.960346132
#Sta/Elev= 30
9749.0671343.1929768.486  1342.39798.8321339.2429819.1911337.9699829.3711336.445
9839.5511334.0959860.2051327.9799870.5871323.876 9880.971319.1459891.3521317.811
9922.8861317.0249933.6571316.3439976.7371316.1149987.4421313.608 9997.951306.847
9998.6821306.83510008.481308.962 10013.91313.22110019.32  1316.810030.431321.308
10041.541323.76910052.651328.48510063.761333.94810071.651336.364 10107.91344.723
 10118.81346.69110172.691345.66110183.591346.459 10232.41344.43510250.971343.048
#Mann= 3 , 0 , 0
9749.067   0.075       09749.067   0.075       010250.97   0.075       0
#XS Ineff= 2 , 0
       0                               0
Bank Sta=9749.067,10250.97
Exp/Cntr=0.3,0.1

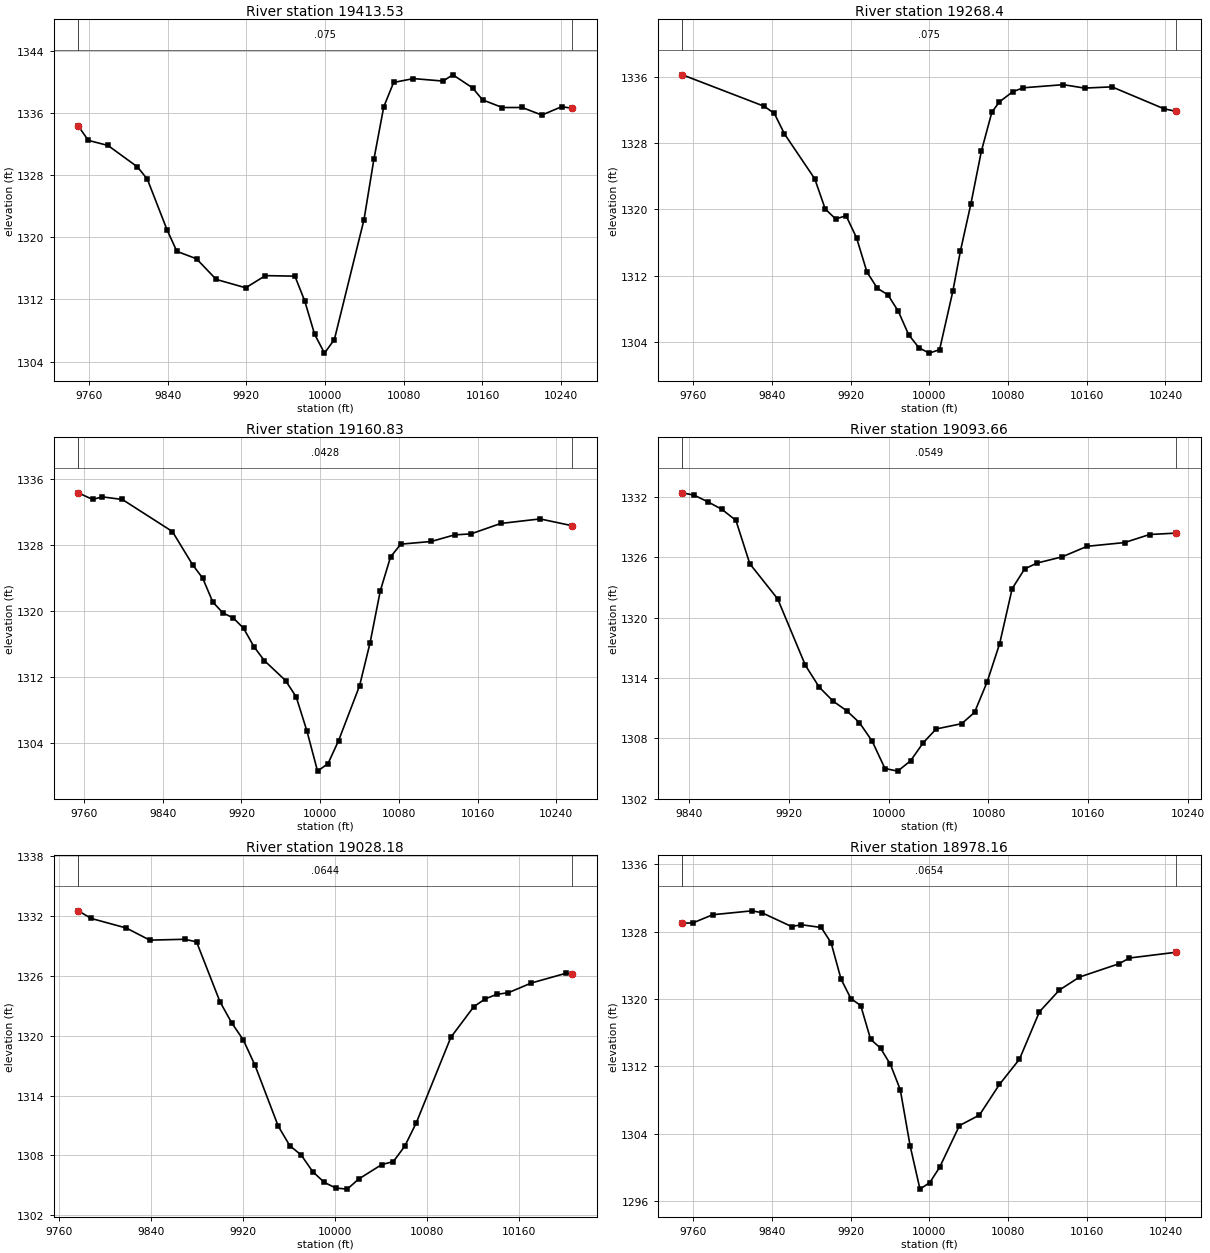
Type RM Length L Ch R = 1 ,19413.53,145.122700,145.122700,145.122700
XS GIS Cut Line= 6
748774.749955844756272.916347238748886.046853591 756273.21708991
749001.827136825756275.679794898749024.624577225756273.829639581
749178.871514603756260.279843779749275.431885786756249.627863948
#Sta/Elev= 30
9749.0241334.3239759.274 1332.479779.2741331.8139809.274 1329.059819.2741327.475
9839.2741320.9669849.2741318.1899869.2761317.2259889.2811314.5729919.2881313.493
9939.2921315.0619969.2991314.9929979.3111311.7929989.3441307.5069999.3781305.085
10009.421306.83710039.53 1322.2610049.571330.01410059.611336.77910069.651339.921
10089.731340.42110119.841340.10110129.881340.90510149.951339.22610160.011337.686
10180.131336.69810200.25  1336.710220.371335.72610240.491336.80510250.991336.601
#Mann= 3 , 0 , 0
9749.024   0.075       09749.024   0.075       010250.99   0.075       0
#XS Ineff= 2 , 0
       0                               0
Bank Sta=9749.024,10250.99
Exp/Cntr=0.3,0.1

Type RM Length L Ch R = 1 , 19268.4,107.569700,107.569700,107.569700
XS GIS Cut Line= 6
748732.834219352756339.310760961748797.789303195756347.833189819
748864.842811424756363.277642171 749108.48483156756446.300681328
749153.896115464756455.305152217749217.368179363756461.265719962
#Sta/Elev= 30
9749.0781336.2759832.2521332.4689842.513  1331.69852.7751329.1329883.566  1323.7
9894.1731320.056 9904.781318.8459915.3871319.2319925.9941316.5859936.6011312.431
9947.2081310.4549957.8151309.6839968.4221307.6939979.0191304.8429989.4941303.258
9999.9641302.61910010.441303.03910023.871310.08310031.551314.93910042.221320.656
10052.881327.03210063.55 1331.7510071.181332.99810084.881334.23810095.551334.708
10136.261335.08510157.72 1334.6710185.611334.82110238.511332.16910250.931331.855
#Mann= 3 , 0 , 0
9749.078   0.075       09749.078   0.075       010250.93   0.075       0
#XS Ineff= 2 , 0
       0                               0
Bank Sta=9749.078,10250.93
Exp/Cntr=0.3,0.1

Type RM Length L Ch R = 1 ,19160.83,67.170400,67.170400,67.170400
XS GIS Cut Line= 6
748690.627484075756435.206060849748835.122719412756462.476701348
748974.891327834756514.836503074749023.885251221756528.818877025
749096.800811665756539.318178018749177.462381458 756540.79408236
#Sta/Elev= 30
9754.0941334.3789768.6221333.579 9778.731333.8859798.9461333.5689849.8041329.669
9870.3381325.6349880.6051323.9929890.8711321.0989901.1381319.7699911.6571319.159
9922.1791317.8979932.701 1315.669943.2231313.9789964.7791311.5489975.6381309.556
9986.4971305.4239997.3551300.52610007.991301.44410018.671304.21910040.041310.902
10050.721316.13210061.121322.46110071.521326.57110081.921328.13510112.86 1328.46
10136.561329.26210153.331329.38510183.481330.65110223.511331.20510255.971330.379
#Mann= 3 , 0 , 0
9754.094  0.0428       09754.094  0.0428       010255.97  0.0428       0
#XS Ineff= 2 , 0
       0                               0
Bank Sta=9754.094,10255.97
Exp/Cntr=0.3,0.1

Type RM Length L Ch R = 1 ,19093.66,65.485700,65.485700,65.485700
XS GIS Cut Line= 4
748746.547757953756491.736947909748859.394980192756547.075489566
748970.072063506 756572.03208679749126.322063506756576.372364581
#Sta/Elev= 30
9834.8991332.3729844.3131332.1389855.4511331.4689866.5881330.7269877.7261329.636
9888.8641325.3319911.1391321.8559933.4141315.2469944.5521313.074 9955.69 1311.69
 9966.331310.7629976.5821309.5829986.8331307.7379997.084 1305.0210007.33 1304.76
10017.591305.78610027.841307.58910038.091308.94310058.591309.46910068.84 1310.59
10078.971313.62510088.971317.41810098.981322.86810108.981324.82710118.991325.408
10138.991326.019   101591327.06610189.011327.43710209.021328.23510230.351328.377
#Mann= 3 , 0 , 0
9834.899  0.0549       09834.899  0.0549       010230.35  0.0549       0
#XS Ineff= 2 , 0
       0                               0
Bank Sta=9834.899,10230.35
Exp/Cntr=0.3,0.1

Type RM Length L Ch R = 1 ,19028.18,50.019500,50.019500,50.019500
XS GIS Cut Line= 3
748673.848105222  756593.7334757 748831.18317467756624.115420118
749100.280396849756607.839378461
#Sta/Elev= 30
 9776.651332.5439788.0081331.7769818.5621330.8159838.9321329.6019869.4861329.688
9879.6711329.423 9900.041323.4159910.2251321.3029920.4091319.5739930.5941317.018
9950.7341310.9339960.7521308.979 9970.771308.0249980.7891306.3619990.8071305.287
10000.831304.71710010.841304.60710020.861305.626 10040.91307.07510050.921307.367
10060.931308.92410070.951311.26810101.011319.84610121.041322.92710131.061323.713
10141.081324.161 10151.11324.32410171.14  1325.310201.191326.27310206.481326.207
#Mann= 3 , 0 , 0
 9776.65  0.0644       0 9776.65  0.0644       010206.48  0.0644       0
#XS Ineff= 2 , 0
       0                               0
Bank Sta=9776.65,10206.48
Exp/Cntr=0.3,0.1

Type RM Length L Ch R = 1 ,18978.16,145.122700,145.122700,145.122700
XS GIS Cut Line= 6
748644.271585515756688.525746002748741.563617258756683.290922797
748868.611763727756671.188726249748918.344527394756669.128936237
749062.355291101756642.815605492749142.020069363756629.869225732
#Sta/Elev= 30
9749.0221328.9879759.7661329.0339779.7951329.9989819.8531330.4619829.8671330.235
9859.9521328.5949869.9971328.8079890.0881328.4859900.1331326.6689910.1781322.377
9920.2241320.0479930.2691319.2129940.314 1315.219950.3591314.1589960.4051312.232
 9970.451309.233 9980.471302.5689990.4761297.42310000.481298.20110010.491300.018
10030.621304.96710050.951306.21510071.291309.85210091.621312.84710111.95 1318.48
10132.281321.06610152.611322.59610193.191324.19510203.331324.85910250.961325.546
#Mann= 3 , 0 , 0
9749.022  0.0654       09749.022  0.0654       010250.96  0.0654       0
#XS Ineff= 2 , 0
       0                               0
Bank Sta=9749.022,10250.96
Exp/Cntr=0.3,0.1