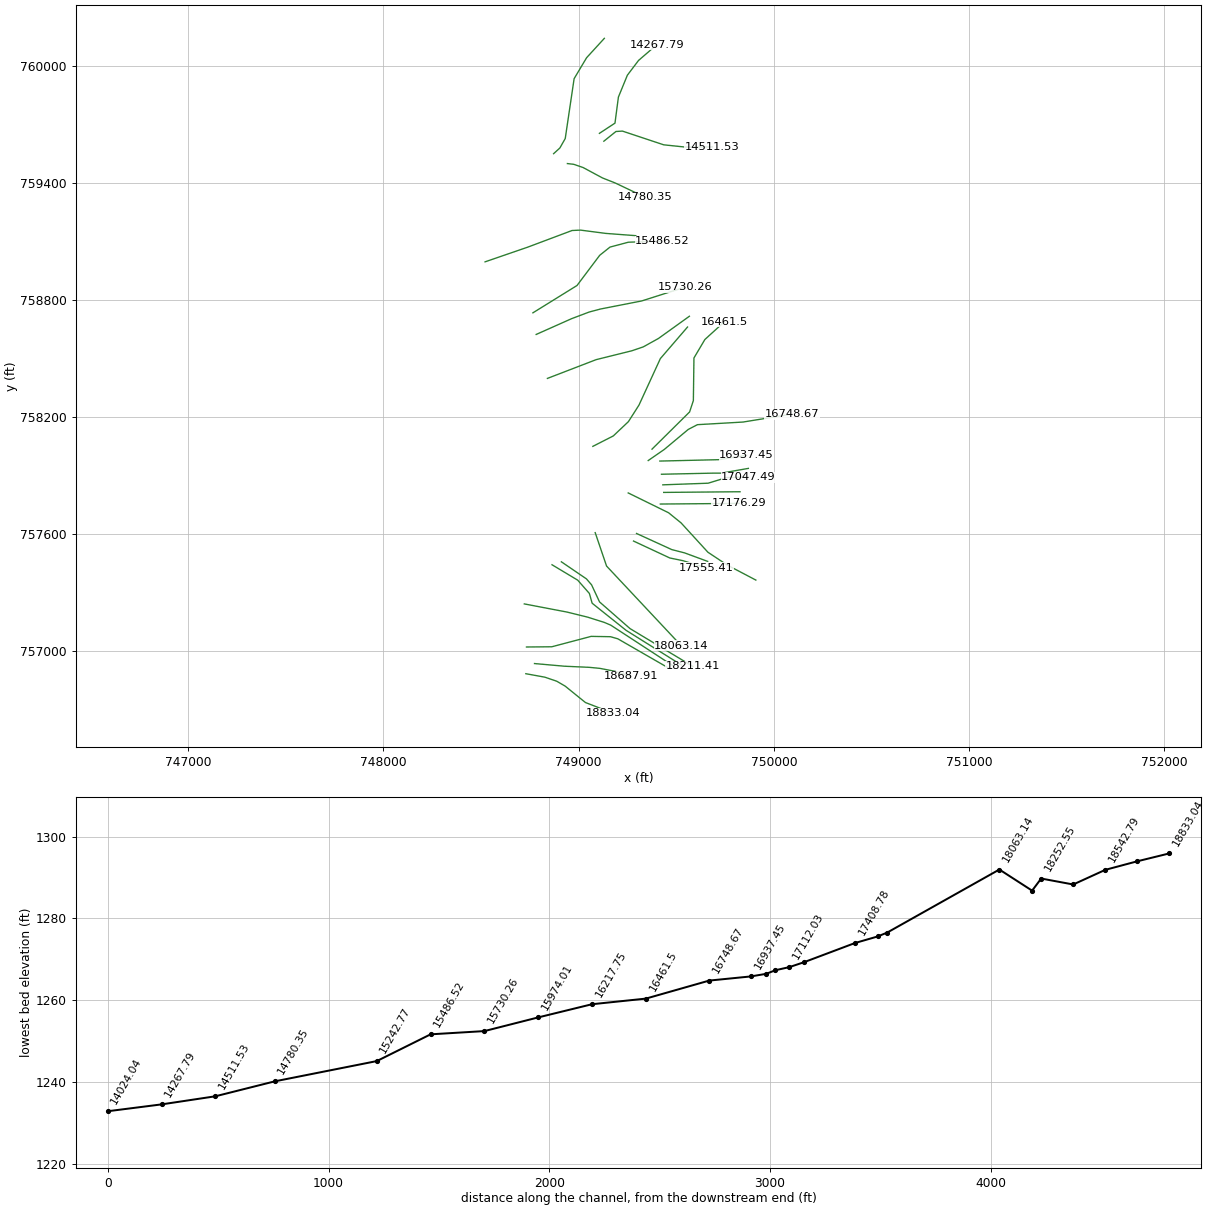
HEC-RAS study 14313_ras.prj: 14313

--- 14313_ras.g01 (geometry) --- (continued)

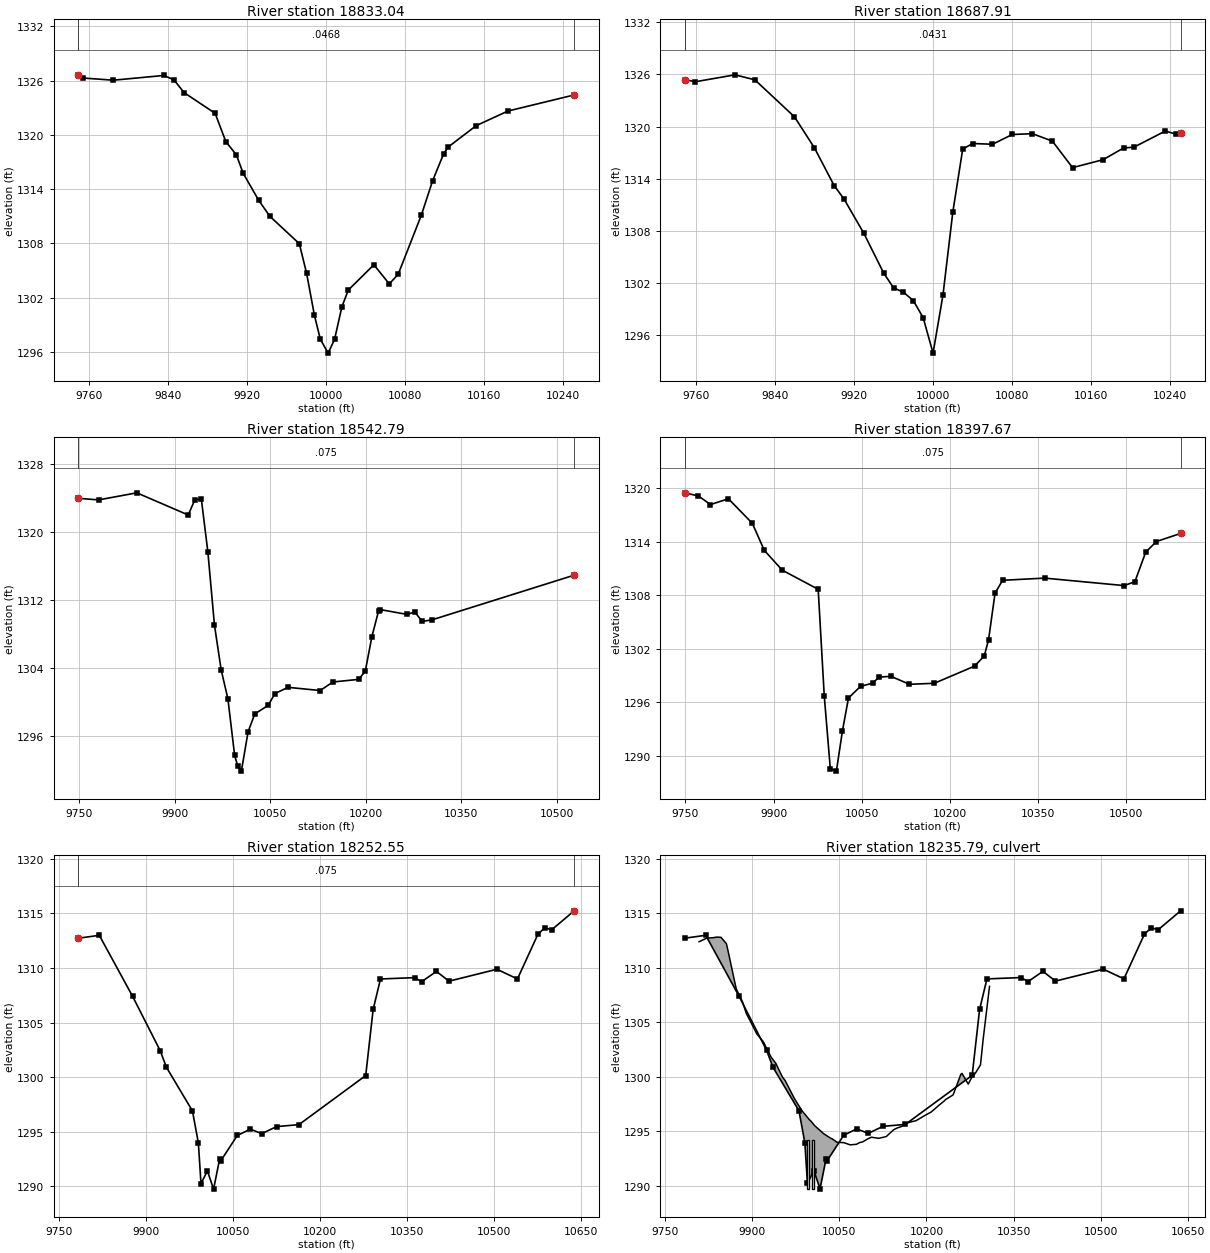
Type RM Length L Ch R = 1 ,18833.04,145.122600,145.122600,145.122600
XS GIS Cut Line= 6
748729.903609788756885.071287637748827.368908915756867.306358336
748887.877918002756846.698006918748931.110609089756821.694381716
749035.170754433 756737.50490616749178.829671028756681.908090016
#Sta/Elev= 30
9749.069 1326.659754.2261326.2939784.5871326.0579835.5281326.5799845.7581326.106
9856.1421324.678 9887.551322.396 9898.311319.2729909.0691317.7919915.8581315.776
9931.4471312.8069942.8971311.0099972.7621307.9759980.1031304.7119987.9941300.081
9994.0081297.41410001.941295.87710008.461297.41310015.831300.99510022.311302.853
10048.221305.645 10063.81303.53410072.761304.58210096.331311.15510107.611314.924
10118.891317.93610123.631318.684 10151.81321.03210183.911322.64610250.931324.425
#Mann= 3 , 0 , 0
9749.069  0.0468       09749.069  0.0468       010250.93  0.0468       0
#XS Ineff= 2 , 0
       0                               0
Bank Sta=9749.069,10250.93
Exp/Cntr=0.3,0.1

Type RM Length L Ch R = 1 ,18687.91,145.122700,145.122700,145.122700
XS GIS Cut Line= 6
748774.381252075 756937.04549238 748928.22687086756923.421416321
749055.801307031756917.659837006749109.229502195756912.426158768
749187.293387306756897.274684412749269.665235552756870.805514246
#Sta/Elev= 30
9749.0161325.3879759.6771325.1469799.8331325.9419819.9111325.3699860.0681321.111
9880.1461317.5659900.224 1313.219910.244 1311.669930.2661307.7249950.288 1303.17
9960.2991301.464 9970.311300.9539980.3211299.9999990.3321298.02510000.341293.953
10010.35 1300.6110020.361310.17910030.371317.40810040.411318.04710060.511317.961
 10080.61319.08310100.831319.176 10121.11318.32410141.561315.27410172.421316.185
 10193.21317.53210203.681317.62310235.441319.47910246.031319.13210250.961319.297
#Mann= 3 , 0 , 0
9749.016  0.0431       09749.016  0.0431       010250.96  0.0431       0
#XS Ineff= 2 , 0
       0                               0
Bank Sta=9749.016,10250.96
Exp/Cntr=0.3,0.1

Type RM Length L Ch R = 1 ,18542.79,145.122600,145.122600,145.122600
XS GIS Cut Line= 6
748733.235125363757021.866872922748863.056490391757023.019059584
749064.509981275757076.266390935749163.262298107757074.568491355
749200.873752922757063.944527775749461.608521849756913.828961805
#Sta/Elev= 30
9749.0771323.9299780.8451323.7429840.8511324.573 9921.541321.9679931.807 1323.75
9942.0731323.852 9952.341317.6119962.7061309.0069973.2551303.7439983.8041300.342
9994.3531293.699    99991292.495 10004.9 1291.8610015.441296.48510025.971298.581
10047.031299.59910057.561300.97610078.111301.70910128.531301.33410148.531302.336
10188.941302.64510199.331303.60910209.721307.67110220.111310.66910222.331310.855
10264.181310.29110277.131310.55310288.671309.45210304.271309.64810527.081314.893
#Mann= 3 , 0 , 0
9749.077   0.075       09749.077   0.075       010527.08   0.075       0
#XS Ineff= 2 , 0
       0                10105.83       0
Bank Sta=9749.077,10527.08
Exp/Cntr=0.3,0.1

Type RM Length L Ch R = 1 ,18397.67,145.122700,145.122700,145.122700
XS GIS Cut Line= 6
748722.123883665757242.542465419748940.998410553757200.751613468
749045.958031416757174.914808795  749132.0513708757147.751750603
749164.749038756757133.813355073749488.735257983756922.509517357
#Sta/Elev= 30
9749.0211319.5089772.3111319.1569792.6721318.1889823.2141318.8439863.9371316.084
9884.2981313.049 9914.84 1310.839975.9711308.684 9986.271296.7449996.5691288.574
10006.921288.28610017.211292.795 10027.51296.48910048.091297.80110068.671298.157
10079.591298.83310099.781298.92310131.061298.02710173.46 1298.1410241.921300.062
10258.551301.211 10265.81303.00810276.851308.25110289.671309.69510361.31 1309.94
10496.52  1309.110514.821309.54310533.131312.84410551.431314.046 10592.61314.951
#Mann= 3 , 0 , 0
9749.021   0.075       09749.021   0.075       0 10592.6   0.075       0
#XS Ineff= 2 , 0
       0                10096.34       0
Bank Sta=9749.021,10592.6
Exp/Cntr=0.3,0.1

Type RM Length L Ch R = 1 ,18252.55,41.138200,41.138200,41.138200
XS GIS Cut Line= 6
748864.023566782757443.076891348748995.805907756757364.007486939
749055.389241099757296.090820283749069.555907756757246.090820253
749243.616057515757107.104691312749527.797757953756929.019934028
#Sta/Elev= 30
9783.5041312.7189819.6281312.9839876.9481307.4049924.5851302.4219935.2581300.905
9980.1651296.901 9990.341293.9749994.8861290.24210005.891291.41110016.561289.741
10026.981292.49110028.791292.31710057.421294.65310079.811295.23410099.581294.822
10125.171295.46910163.561295.64410278.731300.14210291.531306.19210304.191308.986
10363.011309.109   103751308.73710400.681309.679 10422.21308.78410504.811309.876
10540.21 1308.9910575.621313.09410587.421313.67610599.22 1313.4910637.931315.227
#Mann= 3 , 0 , 0
9783.504   0.075       09783.504   0.075       010637.93   0.075       0
#XS Ineff= 2 , 0
       0                10076.82       0
Bank Sta=9783.504,10637.93
Exp/Cntr=0.3,0.1

Type RM Length L Ch R = 2 ,18235.79,,,
Bridge Culvert--1,0,-1,-1, 0
Deck Dist Width WeirC Skew NumUp NumDn MinLoCord MaxHiCord MaxSubmerge Is_Ogee
5.069,31,2.6,0,76,76, , , 0.95, 0, 0,0,,
 9808.17 9808.84 9821.08 9821.17 9833.51 9838.17 9845.84 9855.26 9858.17 9870.50
 9872.35 9882.83 9889.44 9895.16 9906.53 9907.49 9917.96 9919.82 9923.62 9932.16
 9940.71 9944.49 9951.79 9956.65 9957.70 9970.48 9972.18 9984.31 9986.66 9998.13
10001.1410007.0910011.1910018.6010022.8310034.4610038.1510046.1010057.7010057.74
10058.0110068.5010079.2410084.9710089.9910098.5110101.8010105.0010117.7410117.84
10130.6810133.6810143.5210149.6210156.3710165.5610169.2110181.5010182.0510194.89
10197.4410207.7310213.3810220.5710229.3210233.4110245.2610246.2610259.1010261.20
10271.9410277.1410284.7810293.0810297.6210308.61
 1312.40 1312.41 1312.72 1312.72 1312.77 1312.82 1312.80 1312.21 1311.52 1308.47
 1308.04 1306.90 1305.82 1305.24 1304.05 1303.95 1303.28 1303.13 1302.71 1301.82
 1301.21 1300.78 1299.99 1299.65 1299.53 1298.21 1298.03 1296.99 1296.82 1296.08
 1295.93 1295.54 1295.34 1295.00 1294.79 1294.39 1294.30 1294.00 1293.97 1293.97
 1293.96 1293.77 1293.82 1293.98 1294.04 1294.31 1294.39 1294.47 1294.37 1294.37
 1294.53 1294.68 1295.16 1295.32 1295.44 1295.74 1295.82 1295.98 1295.99 1296.39
 1296.47 1296.77 1297.02 1297.36 1297.74 1297.94 1298.33 1298.40 1300.23 1300.32
 1299.34 1299.87 1300.39 1301.11 1303.44 1308.30
                                                                                
                                                                                
                                                                                
                                                                                
                                                                                
                                                                                
                                                                                
                                                
 9808.17 9808.84 9821.08 9821.17 9833.51 9838.17 9845.84 9855.26 9858.17 9870.50
 9872.35 9882.83 9889.44 9895.16 9906.53 9907.49 9917.96 9919.82 9923.62 9932.16
 9940.71 9944.49 9951.79 9956.65 9957.70 9970.48 9972.18 9984.31 9986.66 9998.13
10001.1410007.0910011.1910018.6010022.8310034.4610038.1510046.1010057.7010057.74
10058.0110068.5010079.2410084.9710089.9910098.5110101.8010105.0010117.7410117.84
10130.6810133.6810143.5210149.6210156.3710165.5610169.2110181.5010182.0510194.89
10197.4410207.7310213.3810220.5710229.3210233.4110245.2610246.2610259.1010261.20
10271.9410277.1410284.7810293.0810297.6210308.61
 1312.40 1312.41 1312.72 1312.72 1312.77 1312.82 1312.80 1312.21 1311.52 1308.47
 1308.04 1306.90 1305.82 1305.24 1304.05 1303.95 1303.28 1303.13 1302.71 1301.82
 1301.21 1300.78 1299.99 1299.65 1299.53 1298.21 1298.03 1296.99 1296.82 1296.08
 1295.93 1295.54 1295.34 1295.00 1294.79 1294.39 1294.30 1294.00 1293.97 1293.97
 1293.96 1293.77 1293.82 1293.98 1294.04 1294.31 1294.39 1294.47 1294.37 1294.37
 1294.53 1294.68 1295.16 1295.32 1295.44 1295.74 1295.82 1295.98 1295.99 1296.39
 1296.47 1296.77 1297.02 1297.36 1297.74 1297.94 1298.33 1298.40 1300.23 1300.32
 1299.34 1299.87 1300.39 1301.11 1303.44 1308.30
                                                                                
                                                                                
                                                                                
                                                                                
                                                                                
                                                                                
                                                                                
                                                
BR Coef=-1 , 0 , 0 ,, 0 ,,,0.8,-1,,0,
WSPro=,,,, 1 ,,,, 0 ,,,, 0 ,,,,-1 ,-1 ,-1 , 0 , 0 , 0 , 0 , 0
Multiple Barrel Culv=2,4.5,4.5,31,0.013,0.4,1,58,1,1289.71,1288.31,2,Culvert #1, 0, 5.069
 9995.50 9995.5010004.5010004.50
Culvert Bottom n=0.013
BC Design=,, 0 ,, 0 ,,,,,,

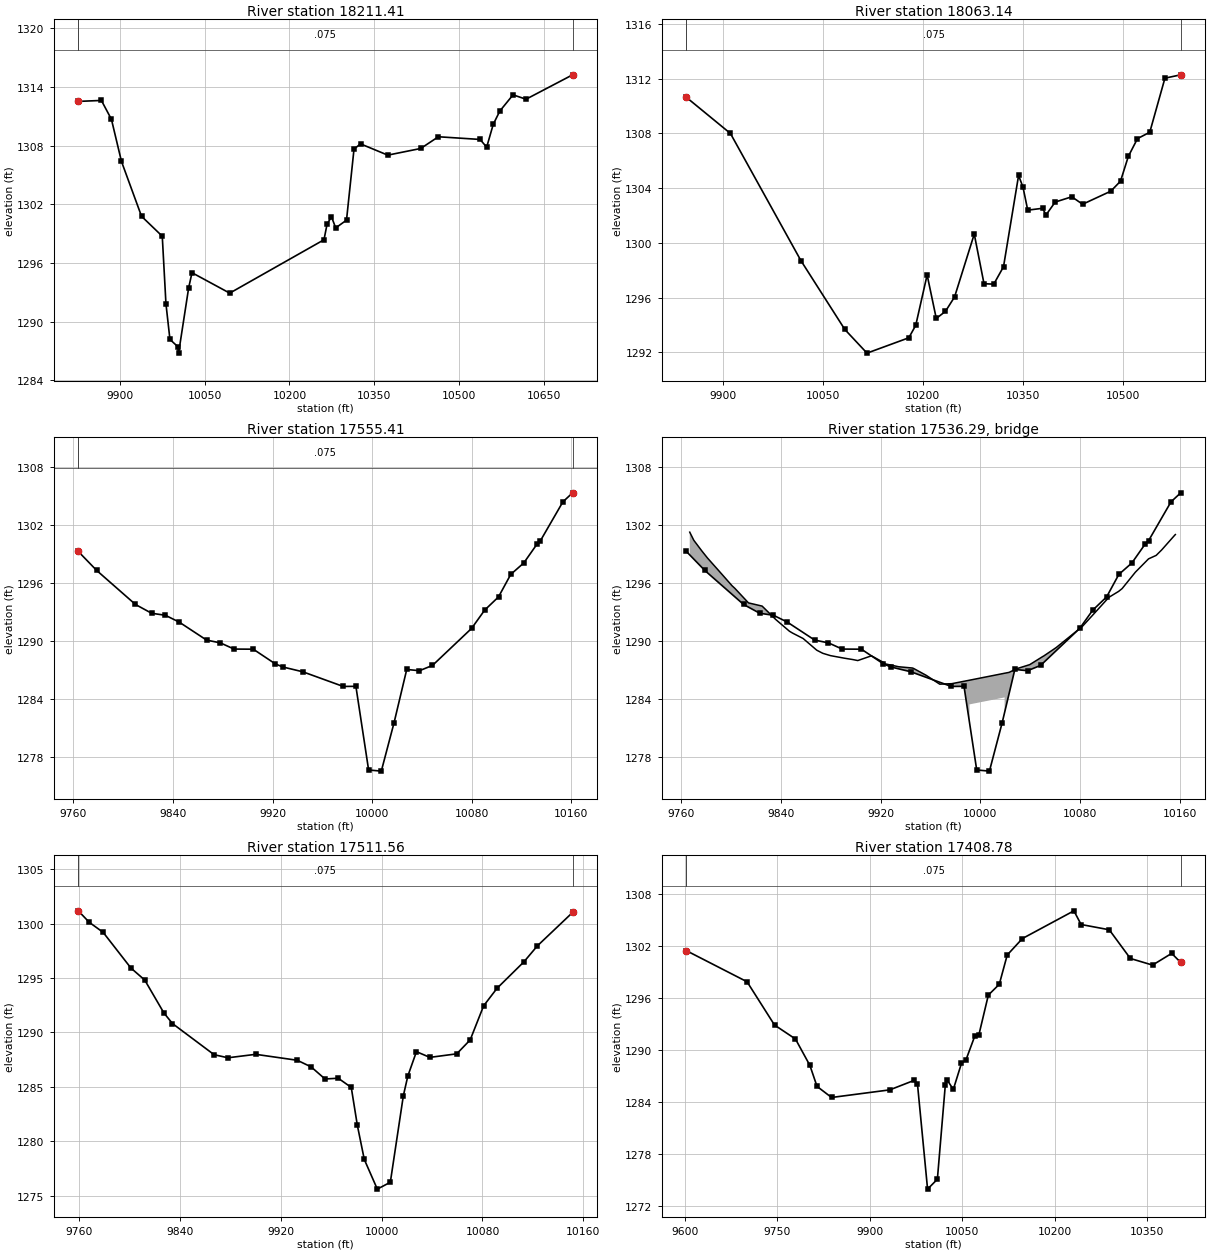
Type RM Length L Ch R = 1 ,18211.41,148.269000,148.269000,148.269000
XS GIS Cut Line= 6
748912.091972291757458.049017623749040.389241099757370.674153611
 749066.63924104757340.257486939749107.472574413757252.757486954
749263.666497141757116.057319239749585.306438535756922.509517357
#Sta/Elev= 30
 9826.131312.5119867.0771312.6099884.8421310.6819902.6081306.3749938.1381300.768
9974.8341298.7329981.3541291.8239988.4111288.18310002.061287.45610003.721286.782
10021.531293.44810027.441295.00210094.231292.91410261.081298.36910266.621299.979
10274.371300.71510281.811299.58110300.951300.37210314.241307.63810325.761308.171
   103741307.01810432.35  1307.710463.571308.89710537.391308.62210549.061307.833
10560.731310.175 10572.41311.52910595.741313.18210618.731312.73410701.141315.227
#Mann= 3 , 0 , 0
 9826.13   0.075       0 9826.13   0.075       010701.14   0.075       0
#XS Ineff= 2 , 0
       0                10071.84       0
Bank Sta=9826.13,10701.14
Exp/Cntr=0.3,0.1

Type RM Length L Ch R = 1 ,18063.14,507.724600,507.724600,507.724600
XS GIS Cut Line= 4
749085.202604026757607.510474995749124.758036762757491.261644214
749143.445621312757436.366864607749526.712688535757027.761253476
#Sta/Elev= 30
9845.6711310.6259911.7011307.98810017.331298.70210083.171293.67210116.431291.942
10179.141293.06310189.511293.97410206.571297.65510220.281294.47410233.99 1294.99
 10247.71296.04510277.221300.63810291.831297.01310306.451296.97910321.071298.252
10343.67 1304.92 10350.31304.05910357.381302.38510379.54 1302.52 10384.81302.034
10398.521302.97610423.391303.36110439.651302.81710481.861303.76910496.471304.502
 10508.21306.31410521.91 1307.6110540.321308.07610563.041312.02510586.681312.269
#Mann= 3 , 0 , 0
9845.671   0.075       09845.671   0.075       010586.68   0.075       0
#XS Ineff= 2 , 0
       0                10068.74       0
Bank Sta=9845.671,10586.68
Exp/Cntr=0.3,0.1

Type RM Length L Ch R = 1 ,17555.41,43.851900,43.851900,43.851900
XS GIS Cut Line= 4
 749281.60046792757564.418366566749467.433801264 757477.75169988
749534.517134577757464.001699895749652.433801264757427.335033223
#Sta/Elev= 30
9763.9471299.2579778.7321297.294 9809.891293.7779822.8681292.8689833.902 1292.66
9844.9361291.9619867.0041290.0959878.038 1289.819889.0721289.1689904.5281289.154
9922.174 1287.649928.1871287.3189944.2421286.8219976.7191285.3069986.9271285.317
9997.1351276.67410007.341276.55410017.551281.54510027.76 1287.0610037.981286.932
10048.451287.47910079.871291.30710090.341293.19210101.471294.55910111.291296.884
10121.761298.06710132.231299.98610135.151300.36810153.171304.38110160.961305.314
#Mann= 3 , 0 , 0
9763.947   0.075       09763.947   0.075       010160.96   0.075       0
#XS Ineff= 2 , 0
       09915.191                       0
Bank Sta=9763.947,10160.96
Exp/Cntr=0.3,0.1

Type RM Length L Ch R = 3 ,17536.29,,,
BEGIN DESCRIPTION:
END DESCRIPTION:
Bridge Culvert--1,0,-1,-1, 0
Deck Dist Width WeirC Skew NumUp NumDn MinLoCord MaxHiCord MaxSubmerge Is_Ogee
10.607050,22.637800,2.6,0, 55, 55, , , 0.95, 0, 0,0,,
 9766.65 9769.92 9776.37 9780.89 9791.87 9800.65 9802.84 9813.81 9824.79 9824.94
 9835.76 9846.74 9849.22 9857.71 9868.68 9873.51 9879.66 9890.63 9897.79 9901.60
 9912.58 9922.08 9923.55 9934.52 9945.50 9946.36 9956.47 9967.44 9970.51 9970.77
 9977.04 9991.32 9991.3210019.5410019.5410023.1710029.2110031.5410039.7310050.33
10050.8110060.9310071.5310080.9610082.1310092.7310103.3310111.1210113.9310124.53
10135.1310141.2810145.7310156.3310156.68
 1301.25 1300.41 1299.31 1298.58 1296.99 1295.71 1295.45 1293.94 1293.61 1293.59
 1292.22 1291.01 1290.82 1290.26 1289.05 1288.73 1288.49 1288.23 1288.08 1287.98
 1288.47 1287.80 1287.64 1287.34 1287.21 1287.17 1286.46 1285.54 1285.56 1285.56
 1285.59 1285.95 1285.95 1286.67 1286.67 1286.76 1287.14 1287.23 1287.56 1288.41
 1288.44 1289.32 1290.42 1291.40 1291.53 1293.02 1294.52 1295.13 1295.42 1297.11
 1298.49 1298.85 1299.42 1300.96 1301.00
  301.25  300.41  299.31  298.58  296.99  295.71  295.45  293.94  293.61  293.59
  292.22  291.01  290.82  290.26  289.05  288.73  288.49  288.23  288.08  287.98
  288.47  287.80  287.64  287.34  287.21  287.17  286.46  285.54  285.56  285.56
  285.59  285.95 1283.45 1284.17  286.67  286.76  287.14  287.23  287.56  288.41
  288.44  289.32  290.42  291.40  291.53  293.02  294.52  295.13  295.42  297.11
  298.49  298.85  299.42  300.96  301.00
 9766.65 9769.92 9776.37 9780.89 9791.87 9800.65 9802.84 9813.81 9824.79 9824.94
 9835.76 9846.74 9849.22 9857.71 9868.68 9873.51 9879.66 9890.63 9897.79 9901.60
 9912.58 9922.08 9923.55 9934.52 9945.50 9946.36 9956.47 9967.44 9970.51 9970.77
 9977.04 9984.60 9984.6010012.8210012.8210023.1710029.2110031.5410039.7310050.33
10050.8110060.9310071.5310080.9610082.1310092.7310103.3310111.1210113.9310124.53
10135.1310141.2810145.7310156.3310156.68
 1301.25 1300.41 1299.31 1298.58 1296.99 1295.71 1295.45 1293.94 1293.61 1293.59
 1292.22 1291.01 1290.82 1290.26 1289.05 1288.73 1288.49 1288.23 1288.08 1287.98
 1288.47 1287.80 1287.64 1287.34 1287.21 1287.17 1286.46 1285.54 1285.56 1285.56
 1285.59 1285.78 1285.78 1286.50 1286.50 1286.76 1287.14 1287.23 1287.56 1288.41
 1288.44 1289.32 1290.42 1291.40 1291.53 1293.02 1294.52 1295.13 1295.42 1297.11
 1298.49 1298.85 1299.42 1300.96 1301.00
  301.25  300.41  299.31  298.58  296.99  295.71  295.45  293.94  293.61  293.59
  292.22  291.01  290.82  290.26  289.05  288.73  288.49  288.23  288.08  287.98
  288.47  287.80  287.64  287.34  287.21  287.17  286.46  285.54  285.56  285.56
  285.59  285.78 1283.28 1284.00  286.50  286.76  287.14  287.23  287.56  288.41
  288.44  289.32  290.42  291.40  291.53  293.02  294.52  295.13  295.42  297.11
  298.49  298.85  299.42  300.96  301.00
BR Coef=-1 , 0 , 0 ,, 0 ,,,0.8,0,1,0,
WSPro=,,,, 1 ,,,, 0 ,,,, 0 ,,,,-1 ,-1 ,-1 , 0 , 0 , 0 , 0 , 0
BC Design=,, 0 ,, 0 ,,,,,,

Type RM Length L Ch R = 1 ,17511.56,102.783600,102.783600,102.783600
XS GIS Cut Line= 4
749297.030270267757603.234044866749477.446936894757520.734044851
749543.696936924757503.650711523749661.196936924 757460.31737818
#Sta/Elev= 30
9759.4151301.1659768.1791300.1079779.1741299.1849801.166 1295.919812.1621294.798
9827.3081291.7839834.1541290.8029867.1421287.9429878.1381287.6589900.1291287.976
9933.1171287.4299944.113 1286.829955.109 1285.71  9965.61285.7799975.9271284.934
9980.7641281.4429986.2541278.3169996.5811275.58610006.911276.21910017.241284.177
10020.81 1285.9910027.61 1288.2210038.261287.69510059.581288.02210070.241289.302
 10080.91292.43510091.561294.04810112.871296.47910123.531297.94510151.451301.015
#Mann= 3 , 0 , 0
9759.415   0.075       09759.415   0.075       010151.45   0.075       0
#XS Ineff= 2 , 0
       09927.865                       0
Bank Sta=9759.415,10151.45
Exp/Cntr=0.3,0.1

Type RM Length L Ch R = 1 ,17408.78,232.491100,232.491100,232.491100
XS GIS Cut Line= 6
749254.388975792757810.892598395749461.073482608757709.359682612
749524.969881471757657.528812448749662.499354093757507.257394787
749760.757339297757441.985578145749908.061346598757364.593058539
#Sta/Elev= 30
 9602.721301.4819701.1671297.8949745.6951292.9079779.6311291.2999803.0641288.253
9814.6431285.8319838.2641284.5529932.686 1285.439971.9051286.5179977.595  1286.1
9993.9721273.98410009.881275.12410022.811286.04710025.971286.54710035.73 1285.48
   100491288.50610056.22 1288.8810070.351291.59310077.311291.80710092.55 1296.36
10110.311297.60610123.181300.98210147.761302.87710231.361306.07510242.981304.498
10288.691303.891 10322.91300.581 10358.91299.81810389.971301.16910404.571300.119
#Mann= 3 , 0 , 0
 9602.72   0.075       0 9602.72   0.075       010404.57   0.075       0
#XS Ineff= 2 , 0
       09948.435                       0
Bank Sta=9602.72,10404.57
Exp/Cntr=0.3,0.1

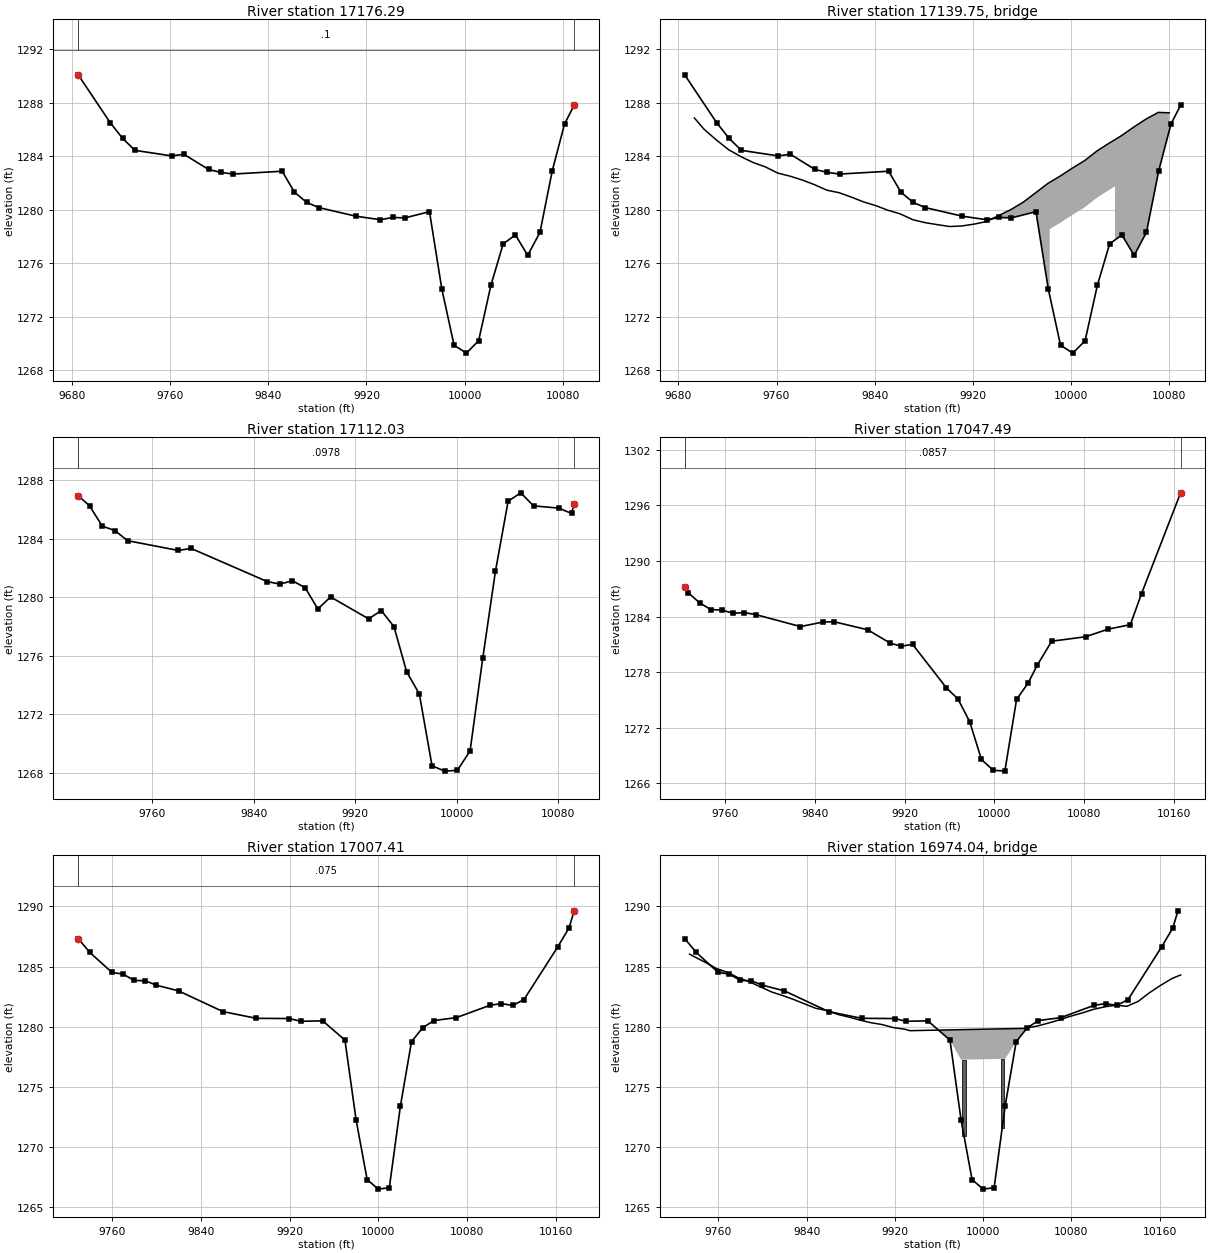
Type RM Length L Ch R = 1 ,17176.29,64.253800,64.253800,64.253800
XS GIS Cut Line= 2
749418.868722727757754.043348025749822.827056071757757.307236921
#Sta/Elev= 30
9685.1871290.0919711.3191286.499 9721.321285.344 9731.321284.4419761.3211284.024
9771.3211284.1459791.322 1283.019801.3221282.7929811.3231282.6659851.3241282.878
9861.324 1281.319871.3251280.5419881.3251280.1549911.3261279.5139931.3271279.248
9941.3271279.4179951.3271279.3869971.328 1279.859981.3281274.0889991.3281269.862
10001.331269.26610011.331270.19110021.331274.33410031.331277.44410041.331278.109
10051.33 1276.5810061.331278.30710071.331282.91310081.331286.41310089.16 1287.82
#Mann= 3 , 0 , 0
9685.187     0.1       09685.187     0.1       010089.16     0.1       0
#XS Ineff= 2 , 0
       09962.105                       0
Bank Sta=9685.187,10089.16
Exp/Cntr=0.3,0.1

Type RM Length L Ch R = 3 ,17139.75,,,
BEGIN DESCRIPTION:
END DESCRIPTION:
Bridge Culvert--1,0,-1,-1, 0
Deck Dist Width WeirC Skew NumUp NumDn MinLoCord MaxHiCord MaxSubmerge Is_Ogee
19.003550,26.246700,2.6,0, 44, 44, , , 0.95, 0, 0,0,,
 9693.13 9700.96 9710.96 9720.96 9730.96 9740.96 9750.96 9760.96 9770.96 9780.96
 9790.96 9800.96 9810.96 9820.96 9830.96 9840.96 9850.96 9860.96 9870.96 9880.96
 9890.96 9900.96 9910.96 9920.96 9930.96 9940.96 9950.96 9960.96 9970.96 9980.96
 9982.53 9982.53 9990.9610000.9610010.9610020.9610030.9610035.6810035.6810040.96
10050.9610060.9610070.9610079.94
 1286.86 1286.02 1285.22 1284.49 1283.97 1283.53 1283.20 1282.74 1282.51 1282.22
 1281.87 1281.46 1281.27 1280.94 1280.58 1280.30 1279.95 1279.68 1279.25 1279.03
 1278.88 1278.74 1278.78 1278.92 1279.11 1279.56 1280.01 1280.56 1281.26 1281.96
 1282.05 1282.05 1282.51 1283.11 1283.67 1284.39 1284.98 1285.24 1285.24 1285.54
 1286.18 1286.78 1287.28 1287.25
  286.86  286.02  285.22  284.49  283.97  283.53  283.20  282.74  282.51  282.22
  281.87  281.46  281.27  280.94  280.58  280.30  279.95  279.68  279.25  279.03
  278.88  278.74  278.78  278.92  279.11  279.56  280.01  280.56  281.26  281.96
  282.05 1278.55 1279.01 1279.61 1280.17 1280.89 1281.48 1281.74  285.24  285.54
  286.18  286.78  287.28  287.25
 9693.13 9700.96 9710.96 9720.96 9730.96 9740.96 9750.96 9760.96 9770.96 9780.96
 9790.96 9800.96 9810.96 9820.96 9830.96 9840.96 9850.96 9860.96 9870.96 9880.96
 9890.96 9900.96 9910.96 9920.96 9930.96 9940.96 9950.96 9960.96 9970.96 9974.80
 9974.80 9980.96 9990.9610000.9610010.9610020.9610027.9510027.9510030.9610040.96
10050.9610060.9610070.9610079.94
 1286.86 1286.02 1285.22 1284.49 1283.97 1283.53 1283.20 1282.74 1282.51 1282.22
 1281.87 1281.46 1281.27 1280.94 1280.58 1280.30 1279.95 1279.68 1279.25 1279.03
 1278.88 1278.74 1278.78 1278.92 1279.11 1279.56 1280.01 1280.56 1281.26 1281.53
 1281.53 1281.96 1282.51 1283.11 1283.67 1284.39 1284.80 1284.80 1284.98 1285.54
 1286.18 1286.78 1287.28 1287.25
  286.86  286.02  285.22  284.49  283.97  283.53  283.20  282.74  282.51  282.22
  281.87  281.46  281.27  280.94  280.58  280.30  279.95  279.68  279.25  279.03
  278.88  278.74  278.78  278.92  279.11  279.56  280.01  280.56  281.26  281.53
 1278.03 1278.46 1279.01 1279.61 1280.17 1280.89 1281.30  284.80  284.98  285.54
  286.18  286.78  287.28  287.25
BR Coef=-1 , 0 , 0 ,, 0 ,,,0.8,0,1,0,
WSPro=,,,, 1 ,,,, 0 ,,,, 0 ,,,,-1 ,-1 ,-1 , 0 , 0 , 0 , 0 , 0
BC Design=,, 0 ,, 0 ,,,,,,

Type RM Length L Ch R = 1 ,17112.03,64.545100,64.545100,64.545100
XS GIS Cut Line= 2
749436.067896575757813.569423921749827.040118843 757817.04164613
#Sta/Elev= 30
9701.4981286.938 9710.431286.242 9720.431284.8579730.431 1284.559740.431 1283.86
9780.4331283.1939790.4331283.3339850.4361281.0689860.4361280.8919870.4361281.122
9880.4371280.6429890.4371279.1919900.4381280.0179930.4391278.5179940.4391279.084
 9950.441277.984 9960.441274.895 9970.441273.3839980.4411268.4779990.441 1268.11
10000.441268.16610010.441269.49210020.441275.83710030.441281.77410040.441286.559
10050.441287.13110060.44 1286.2410080.441286.08510090.451285.71910092.49 1286.39
#Mann= 3 , 0 , 0
9701.498  0.0978       09701.498  0.0978       010092.49  0.0978       0
#XS Ineff= 2 , 0
       09953.681        10047.55       0
Bank Sta=9701.498,10092.49
Exp/Cntr=0.3,0.1

Type RM Length L Ch R = 1 ,17047.49,40.075200,40.075200,40.075200
XS GIS Cut Line= 4
749431.682933211757852.425600365749663.627377629757860.758933708
749758.766266525757889.925600365749869.877377659757892.008933708
#Sta/Elev= 30
9723.5631287.2199726.8821286.5789736.889 1285.499746.8951284.7719756.9021284.705
9766.9081284.3689776.9151284.4399786.9211284.2259826.9471282.932 9846.961283.418
9856.9661283.4529886.9861282.5819906.9991281.1439917.0051280.8119927.0121281.012
9957.0931276.3349967.5521275.1079978.0121272.6649988.4711268.5839998.9311267.425
10009.391267.32610019.851275.06610030.311276.86310038.361278.77510051.23 1281.35
10081.41 1281.8310101.411282.64710121.411283.13410131.411286.487 10166.31297.368
#Mann= 3 , 0 , 0
9723.563  0.0857       09723.563  0.0857       0 10166.3  0.0857       0
#XS Ineff= 2 , 0
       09965.067        10047.05       0
Bank Sta=9723.563,10166.3
Exp/Cntr=0.3,0.1

Type RM Length L Ch R = 1 ,17007.41,69.960100,69.960100,69.960100
XS GIS Cut Line= 4
749424.560587922757906.630018932749686.898550907757912.266593006
749730.648550907757912.266593006749869.537439832757936.572148574
#Sta/Elev= 30
9729.4951287.3279739.9371286.1749759.9421284.5069769.9441284.3719779.9461283.842
9789.9491283.8159799.9511283.4489819.9561282.9729859.965 1281.259889.972 1280.69
9919.979 1280.679929.9811280.4439949.9861280.476 9969.991278.8749979.9931272.257
9989.995 1267.279999.9951266.471   100101266.588   100201273.398   100301278.745
10040.061279.90410050.211280.50310070.521280.74910100.971281.78110111.131281.912
10121.281281.75910131.431282.25310161.891286.64310172.041288.21710176.641289.637
#Mann= 3 , 0 , 0
9729.495   0.075       09729.495   0.075       010176.64   0.075       0
#XS Ineff= 2 , 0
       09957.039        10049.32       0
Bank Sta=9729.495,10176.64
Exp/Cntr=0.3,0.1

Type RM Length L Ch R = 3 ,16974.04,,,
BEGIN DESCRIPTION:
END DESCRIPTION:
Bridge Culvert--1,0,-1,-1, 0
Deck Dist Width WeirC Skew NumUp NumDn MinLoCord MaxHiCord MaxSubmerge Is_Ogee
8.897400,52.165300,2.6,0, 44, 44, , , 0.95, 0, 0,0,,
 9733.98 9738.39 9748.40 9758.40 9768.41 9778.41 9788.42 9798.43 9808.43 9818.44
 9828.44 9838.45 9848.46 9858.46 9868.47 9878.47 9888.48 9898.49 9908.49 9918.50
 9928.51 9933.79 9949.48 9949.4810036.5710038.6310048.8310050.5210050.5210059.03
10069.2310079.4310082.6710089.6310099.8310110.0310120.2310130.4310133.3710140.63
10150.8310161.0310171.2310179.06
 1286.03 1285.81 1285.34 1284.83 1284.51 1284.05 1283.72 1283.30 1282.88 1282.58
 1282.25 1281.88 1281.52 1281.34 1281.01 1280.79 1280.54 1280.32 1280.17 1279.92
 1279.79 1279.66 1279.69 1279.69 1279.85 1279.87 1280.04 1280.08 1280.08 1280.29
 1280.56 1280.87 1280.95 1281.13 1281.43 1281.64 1281.78 1281.69 1281.81 1282.10
 1282.82 1283.44 1284.00 1284.30
  286.03  285.81  285.34  284.83  284.51  284.05  283.72  283.30  282.88  282.58
  282.25  281.88  281.52  281.34  281.01  280.79  280.54  280.32  280.17  279.92
  279.79  279.66  279.69 1277.19 1277.35 1277.37 1277.54 1277.58  280.08  280.29
  280.56  280.87  280.95  281.13  281.43  281.64  281.78  281.69  281.81  282.10
  282.82  283.44  284.00  284.30
 9733.98 9738.39 9748.40 9758.40 9768.41 9778.41 9788.42 9798.43 9808.43 9818.44
 9828.44 9838.45 9848.46 9858.46 9868.47 9878.47 9888.48 9898.49 9908.49 9918.50
 9928.51 9933.79 9949.48 9949.4810036.5710038.6310048.8310050.5210050.5210059.03
10069.2310079.4310082.6710089.6310099.8310110.0310120.2310130.4310133.3710140.63
10150.8310161.0310171.2310179.06
 1286.03 1285.81 1285.34 1284.83 1284.51 1284.05 1283.72 1283.30 1282.88 1282.58
 1282.25 1281.88 1281.52 1281.34 1281.01 1280.79 1280.54 1280.32 1280.17 1279.92
 1279.79 1279.66 1279.69 1279.69 1279.85 1279.87 1280.04 1280.08 1280.08 1280.29
 1280.56 1280.87 1280.95 1281.13 1281.43 1281.64 1281.78 1281.69 1281.81 1282.10
 1282.82 1283.44 1284.00 1284.30
  286.03  285.81  285.34  284.83  284.51  284.05  283.72  283.30  282.88  282.58
  282.25  281.88  281.52  281.34  281.01  280.79  280.54  280.32  280.17  279.92
  279.79  279.66  279.69 1277.19 1277.35 1277.37 1277.54 1277.58  280.08  280.29
  280.56  280.87  280.95  281.13  281.43  281.64  281.78  281.69  281.81  282.10
  282.82  283.44  284.00  284.30
Pier Skew, UpSta & Num, DnSta & Num=  ,9982.66, 2 ,9982.66, 2 , 0 , 0 , 0 ,,
    3.00    3.00
  279.75 1279.75
    3.00    3.00
  279.75 1279.75
Pier Skew, UpSta & Num, DnSta & Num=  ,10017.34, 2 ,10017.34, 2 , 0 , 0 , 0 ,,
    3.00    3.00
  279.81 1279.81
    3.00    3.00
  279.81 1279.81
BR Coef=-1 , 0 , 0 ,, 0 ,,,0.8,0,1,0,
WSPro=,,,, 1 ,,,, 0 ,,,, 0 ,,,,-1 ,-1 ,-1 , 0 , 0 , 0 , 0 , 0
BC Design=,, 0 ,, 0 ,,,,,,

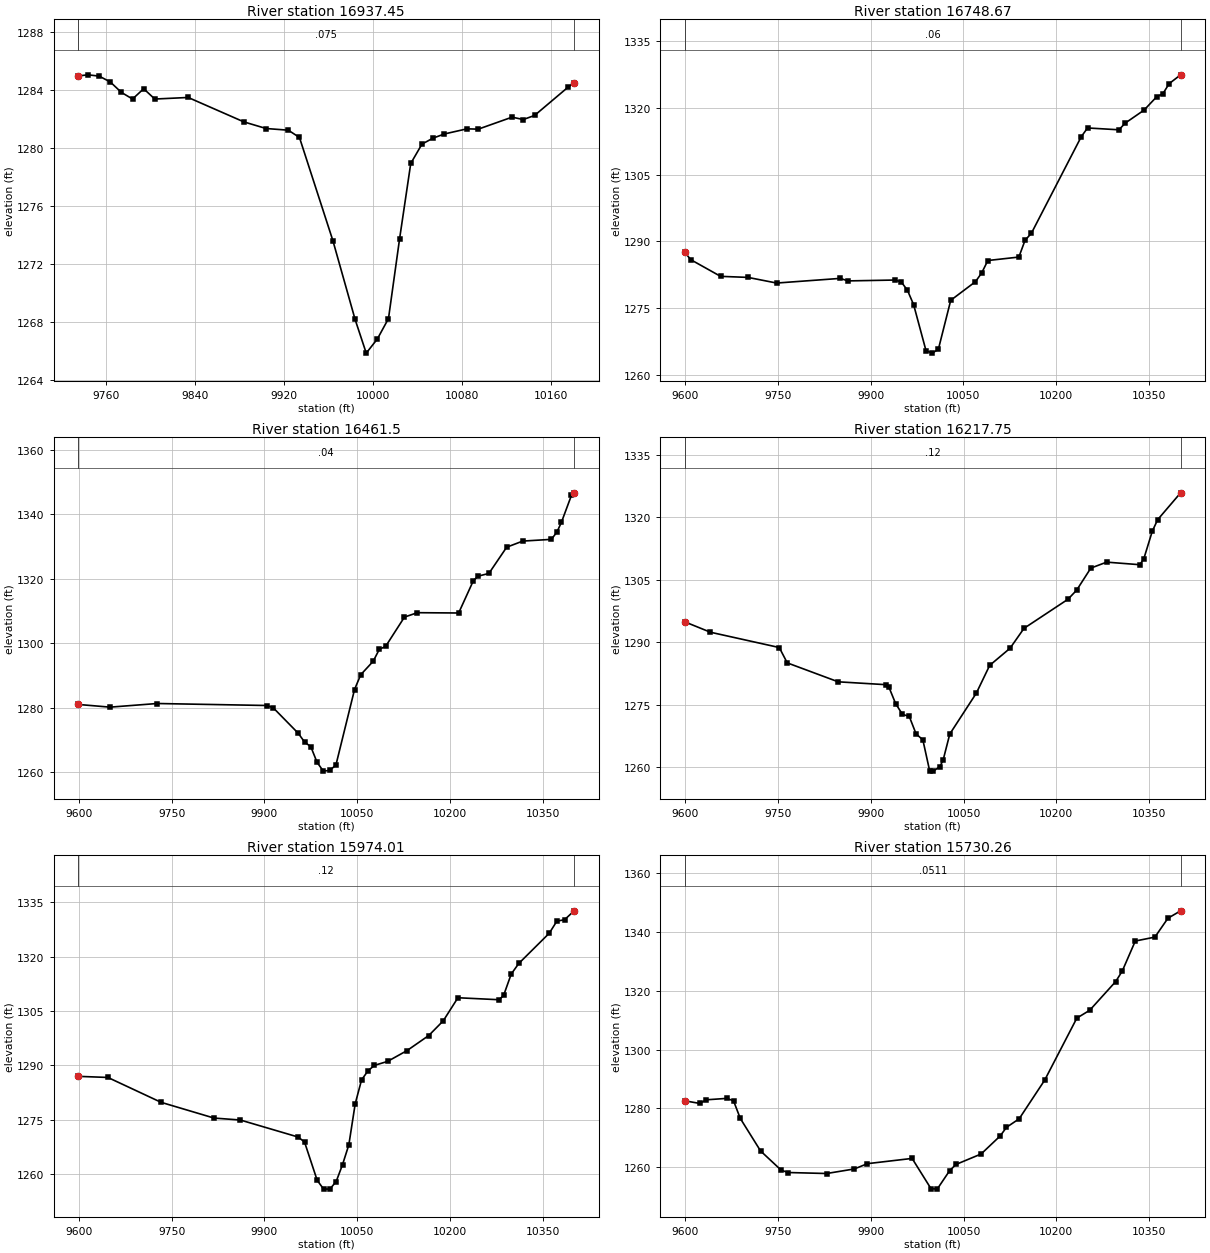
Type RM Length L Ch R = 1 ,16937.45,188.786200,188.786200,188.786200
XS GIS Cut Line= 3
749416.284558429757974.107402354749718.483632519757981.271754204
749860.150299175758003.493976443
#Sta/Elev= 30
9735.3151284.9759744.0331285.0519754.0361284.9629764.0391284.5589774.0421283.836
9784.044 1283.389794.047 1284.09 9804.051283.3799834.0591283.4879884.0731281.802
9904.0781281.3439924.0841281.2279934.0871280.7239964.0951273.6079984.1011268.155
9994.104 1265.8310004.111266.80910014.11 1268.2210024.111273.74110034.111278.929
 10044.21280.26710054.321280.68510064.441280.96810084.681281.32110094.811281.299
10125.171282.127 10135.31281.96410145.421282.24510175.791284.216   101811284.491
#Mann= 3 , 0 , 0
9735.315   0.075       09735.315   0.075       0   10181   0.075       0
#XS Ineff= 2 , 0
       09925.426        10054.97       0
Bank Sta=9735.315,10181
Exp/Cntr=0.3,0.1

Type RM Length L Ch R = 1 ,16748.67,287.169100,287.169100,287.169100
XS GIS Cut Line= 6
749356.729003284757976.802357107749439.033270205 758033.62148841
749561.790105066758136.171421148749608.671527001758160.514863595
749842.025352078758173.965216362750093.270996716758214.595306247
#Sta/Elev= 30
9599.4821287.5059609.2241285.8519657.3731282.1039701.6891281.8669748.0011280.595
9850.9661281.645 9863.341281.0779939.4621281.273 9949.521280.856 9959.551278.969
9969.5511275.7199989.5521265.3749999.5531264.81410009.551265.67610029.551276.711
10069.551280.90510079.571282.867 10089.6 1285.6710139.741286.44610149.791290.245
10159.891291.781 10240.71313.56710250.851315.519 10301.61315.10410311.741316.614
10342.191319.53810362.491322.52610372.641323.22610382.791325.49610401.331327.483
#Mann= 3 , 0 , 0
9599.482    0.06       09599.482    0.06       010401.33    0.06       0
#XS Ineff= 2 , 0
       0                10064.87       0
Bank Sta=9599.482,10401.33
Exp/Cntr=0.3,0.1

Type RM Length L Ch R = 1 , 16461.5,243.745700,243.745700,243.745700
XS GIS Cut Line= 6
749376.170833862758035.146670023749568.732431742758225.702450545
749587.997780531758283.946095317749590.951473574 758502.06165562
749646.919613605758596.673429899749747.054178087758687.722441934
#Sta/Elev= 30
9599.1731281.0849650.4471280.2499726.7331281.3799904.195 1280.769914.5381280.002
9954.8341272.1249964.9231269.4359975.0591267.9699985.1961263.1179995.332 1260.41
10005.471260.63410015.591262.26910045.73 1285.7210055.751290.30910075.821294.464
10085.871298.20310095.911299.07110126.421308.17710147.351309.54210214.061309.447
10237.931319.50810245.75 1320.88   102631321.72310291.681329.84810317.661331.745
10363.921332.282 10372.81334.49710380.151337.53810396.381345.921 10400.81346.711
#Mann= 3 , 0 , 0
9599.173    0.04       09599.173    0.04       0 10400.8    0.04       0
#XS Ineff= 2 , 0
       0                               0
Bank Sta=9599.173,10400.8
Exp/Cntr=0.3,0.1

Type RM Length L Ch R = 1 ,16217.75,243.745600,243.745600,243.745600
XS GIS Cut Line= 6
 749073.32072879758049.520745103749177.938784111758102.819890138
749255.396283888758176.134554563749309.552813492758260.982101948
749418.953616817758498.979414894749558.096863344758660.632318244
#Sta/Elev= 30
9599.1231294.9099640.6331292.4139751.874 1288.749764.7791285.0529847.176  1280.5
9924.647 1279.819929.0671279.2679940.0681275.253 9951.07 1272.689962.0721272.192
9973.0731268.0029984.0751266.5539995.0761259.109   100011259.03910011.671260.128
10016.881261.70610027.631267.95210070.631277.79510092.131284.44810125.081288.565
10147.64 1293.35 10218.61300.32210232.731302.51310255.681307.82210281.291309.258
 10334.9 1308.6410341.281310.02410355.11  1316.710363.831319.47410400.911325.913
#Mann= 3 , 0 , 0
9599.123    0.12       09599.123    0.12       010400.91    0.12       0
#XS Ineff= 2 , 0
       0                               0
Bank Sta=9599.123,10400.91
Exp/Cntr=0.3,0.1

Type RM Length L Ch R = 1 ,15974.01,243.745600,243.745600,243.745600
XS GIS Cut Line= 6
 748840.56581864 758397.47964023749090.595525215758493.719766739
749272.933972416758538.932176751749331.253622421758558.863867001
749409.190855523758602.023437887749567.681415957  758715.8676031
#Sta/Elev= 30
9599.0341286.9379646.8531286.6329732.9491279.7669818.4991275.4279861.0281274.888
9954.6221270.189 9964.861268.8169985.3361258.2459995.5741255.86810005.811255.819
10016.061257.92310026.311262.57610036.551268.068 10046.81279.36110057.091285.954
10067.541288.47210077.991289.97410099.181291.06110130.651294.04810165.781298.208
10189.191302.25310212.941308.62810279.46 1308.0810286.821309.26410299.131315.163
10311.441318.10210360.691326.437   103731329.77210385.321330.14710400.931332.611
#Mann= 3 , 0 , 0
9599.034    0.12       09599.034    0.12       010400.93    0.12       0
#XS Ineff= 2 , 0
       0                               0
Bank Sta=9599.034,10400.93
Exp/Cntr=0.3,0.1

Type RM Length L Ch R = 1 ,15730.26,243.745600,243.745600,243.745600
XS GIS Cut Line= 6
748783.019274483758622.616673153748964.314978595758703.393004899
749054.456409083758737.476084422749112.951510063758752.967874473
749323.312687411758794.131884372749544.411347651758864.548707948
#Sta/Elev= 30
9599.044 1282.559623.1081281.6639634.0561282.8969666.8991283.3759677.8471282.556
9688.794 1276.559721.6371265.467 9754.481259.0159765.4281258.1369828.4341257.795
9873.2931259.3519894.4791261.1539966.6621262.9349997.1211252.67210007.261252.477
10027.531258.80810037.671260.88310078.291264.44410109.061270.56810119.31 1273.52
10139.831276.42610181.041289.56810233.111310.71210253.941313.38410295.981323.171
10306.541326.72410327.661336.96210359.341338.29710380.461344.72810400.961347.244
#Mann= 3 , 0 , 0
9599.044  0.0511       09599.044  0.0511       010400.96  0.0511       0
#XS Ineff= 2 , 0
       09900.749                       0
Bank Sta=9599.044,10400.96
Exp/Cntr=0.3,0.1

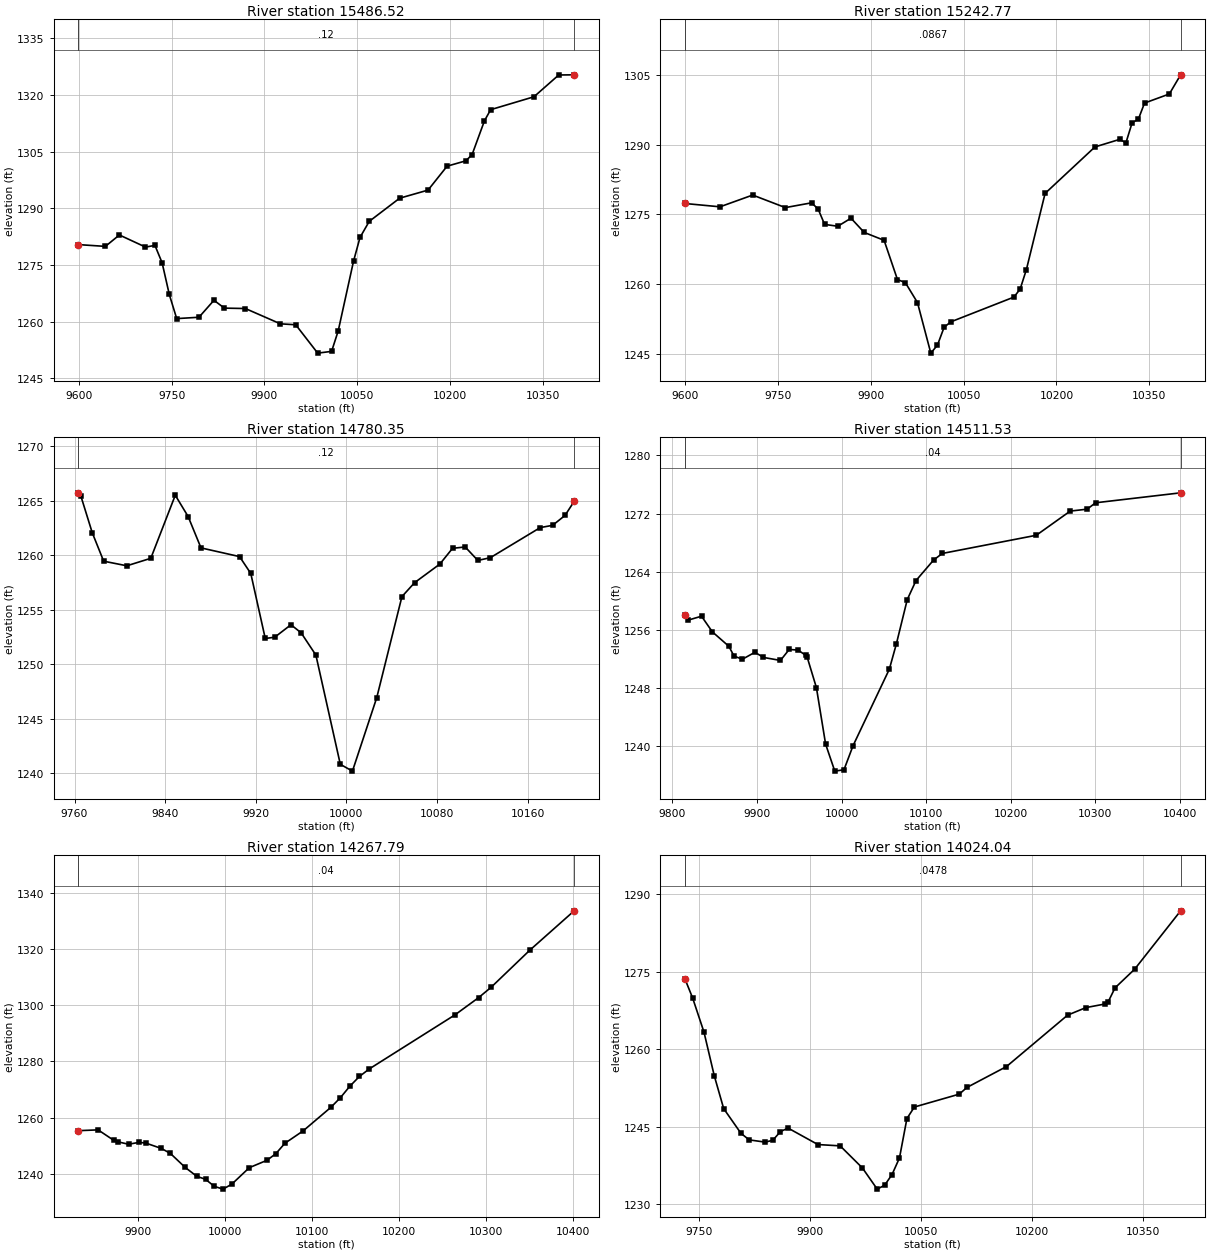
Type RM Length L Ch R = 1 ,15486.52,243.745600,243.745600,243.745600
XS GIS Cut Line= 6
748766.305429631758733.400407415748992.016587082758873.267661272
749108.383200076759028.013587138749161.099321061 759070.08681667
 749255.41544688 759095.07724298 749429.94750839 759100.53600216
#Sta/Elev= 30
 9599.111280.4099642.8641279.935 9665.481282.9589707.7091279.755 9722.981280.196
9734.5851275.593 9746.191267.2139758.1491260.8229794.1591261.1829818.3951265.671
9835.2911263.597 9869.22 1263.499925.7551259.4449950.6291259.1899986.1361251.686
10008.611252.14910019.311257.58110044.151276.07610054.551282.30110069.441286.555
10118.621292.68810164.561294.83410195.341301.16610225.721302.58410235.74 1304.22
10255.781313.18210265.791316.11810335.851319.53810375.85  1325.3 10400.81325.342
#Mann= 3 , 0 , 0
 9599.11    0.12       0 9599.11    0.12       0 10400.8    0.12       0
#XS Ineff= 2 , 0
       09882.982                       0
Bank Sta=9599.11,10400.8
Exp/Cntr=0.3,0.1

Type RM Length L Ch R = 1 ,15242.77,462.416400,462.416400,462.416400
XS GIS Cut Line= 6
748521.196913942758994.483531964748740.211377371759069.884443678
748966.738068871759154.965299656749010.393231658759156.945064932
749139.508007408759140.098727198749293.205535163759128.513545437
#Sta/Elev= 30
9599.0081277.334 9655.91 1276.62 9708.791279.149 9761.67 1276.459803.9741277.477
 9814.551276.1639825.1261272.8369846.429 1272.449867.7841274.1699889.139 1271.11
9921.3441269.4129942.921 1260.989955.7251260.3089975.2881256.0289996.8651245.152
10007.621246.86810018.361250.704 10029.11251.87310131.281257.20310141.361258.927
10151.451263.117 10181.71279.50510262.291289.494 10302.41291.12710312.431290.379
10322.461294.70510332.491295.44810342.521298.93210382.631300.88610400.891305.005
#Mann= 3 , 0 , 0
9599.008  0.0867       09599.008  0.0867       010400.89  0.0867       0
#XS Ineff= 2 , 0
       0                               0
Bank Sta=9599.008,10400.89
Exp/Cntr=0.3,0.1

Type RM Length L Ch R = 1 ,14780.35,268.820500,268.820500,268.820500
XS GIS Cut Line= 6
748942.768035672759497.777826131748974.930380072759494.091145371
 749023.02171993759477.593788074749122.885810996759423.989092526
749188.125796903759398.209311068749342.404444482759324.736964654
#Sta/Elev= 30
9763.3411265.7319765.5751265.4389775.5891262.0829785.7091259.4599806.1671259.037
9827.3271259.7249848.9261265.5099860.2761263.5589871.6251260.6799905.6741259.881
9915.5971258.3339928.3731252.3699936.7411252.4849951.0721253.6299960.023 1252.89
9973.0811250.8439994.6411240.82310005.351240.19810026.821246.94410049.031256.208
 10060.21257.48710082.551259.19710093.72 1260.6410104.891260.76410116.061259.528
10127.09 1259.7810171.141262.54110182.071262.74910193.011263.655 10201.11264.947
#Mann= 3 , 0 , 0
9763.341    0.12       09763.341    0.12       0 10201.1    0.12       0
#XS Ineff= 2 , 0
       0                               0
Bank Sta=9763.341,10201.1
Exp/Cntr=0.3,0.1

Type RM Length L Ch R = 1 ,14511.53,243.745600,243.745600,243.745600
XS GIS Cut Line= 6
749129.577271849759612.396670148749191.487791002759662.030546337
749224.521417528759664.120187297749436.169437706759593.784148246
749545.722932011759582.333994389749685.512486279 759582.97449556
#Sta/Elev= 30
9814.6181258.003 9818.781257.3379834.3851257.8689847.2021255.7189866.7411253.727
9872.8361252.3829882.7281251.9479897.5241252.9069907.6491252.1969927.7391251.784
9938.0421253.2899948.5251253.2149957.4021252.5019959.3911252.2119970.2581248.038
9981.1241240.2729991.9911236.55210002.841236.73810013.631240.06410056.491250.576
10064.791254.05110077.691260.15810088.071262.78210108.841265.59710119.081266.503
10230.311269.007 10270.41272.334 10290.41272.597 10300.41273.47710400.951274.846
#Mann= 3 , 0 , 0
9814.618    0.04       09814.618    0.04       010400.95    0.04       0
#XS Ineff= 2 , 0
       0                               0
Bank Sta=9814.618,10400.95
Exp/Cntr=0.3,0.1

Type RM Length L Ch R = 1 ,14267.79,243.745600,243.745600,243.745600
XS GIS Cut Line= 6
749106.790813506759652.544239581749186.537903249759704.936949864
749204.086036772759838.270354137749249.846248209 759950.12276113
749307.192630976 760025.91303204749399.851301879760105.791348547
#Sta/Elev= 30
9831.8191255.3539854.5041255.6349872.7161251.8759877.5371251.3679889.502 1250.53
9901.4671251.196 9909.141250.9569927.2371249.0219937.4621247.2619954.4241242.295
9967.7731239.1289977.804 1238.079987.8361235.5669997.8681234.57410007.931236.334
10028.051242.20110048.371244.83310058.531247.18810068.881250.87210089.771255.268
10121.581263.63210132.531267.05910143.471271.17810154.411274.62210165.831277.323
10264.231296.55210291.281302.66610305.561306.32610349.981319.51610400.851333.502
#Mann= 3 , 0 , 0
9831.819    0.04       09831.819    0.04       010400.85    0.04       0
#XS Ineff= 2 , 0
       0                               0
Bank Sta=9831.819,10400.85
Exp/Cntr=0.3,0.1

Type RM Length L Ch R = 1 ,14024.04,243.745700,243.745700,243.745700
XS GIS Cut Line= 6
748872.241616838759548.397594489748904.178992664759577.493089231
748931.780419394759625.976700959748977.273816918 759932.56170895
749041.076724769760039.685091678749132.092583984760139.168355168
#Sta/Elev= 30
 9730.481273.6899741.1521269.8959756.4571263.2949770.329 1254.869783.0641248.496
9806.4331243.708 9817.561242.4419839.1041242.0079849.4451242.3619859.7851244.046
9870.1261244.7269910.4651241.5359940.5241241.2829970.5821237.0089990.6221232.901
10000.661233.655 10010.7 1235.7310020.751238.952 10030.81246.56910040.851248.804
10101.591251.30210111.941252.59910165.431256.64310248.021266.60210272.871268.068
10299.061268.77210302.98  1269.210312.15 1271.8810338.761275.51110400.87 1286.81
#Mann= 3 , 0 , 0
 9730.48  0.0478       0 9730.48  0.0478       010400.87  0.0478       0
#XS Ineff= 2 , 0
       0                               0
Bank Sta=9730.48,10400.87
Exp/Cntr=0.3,0.1