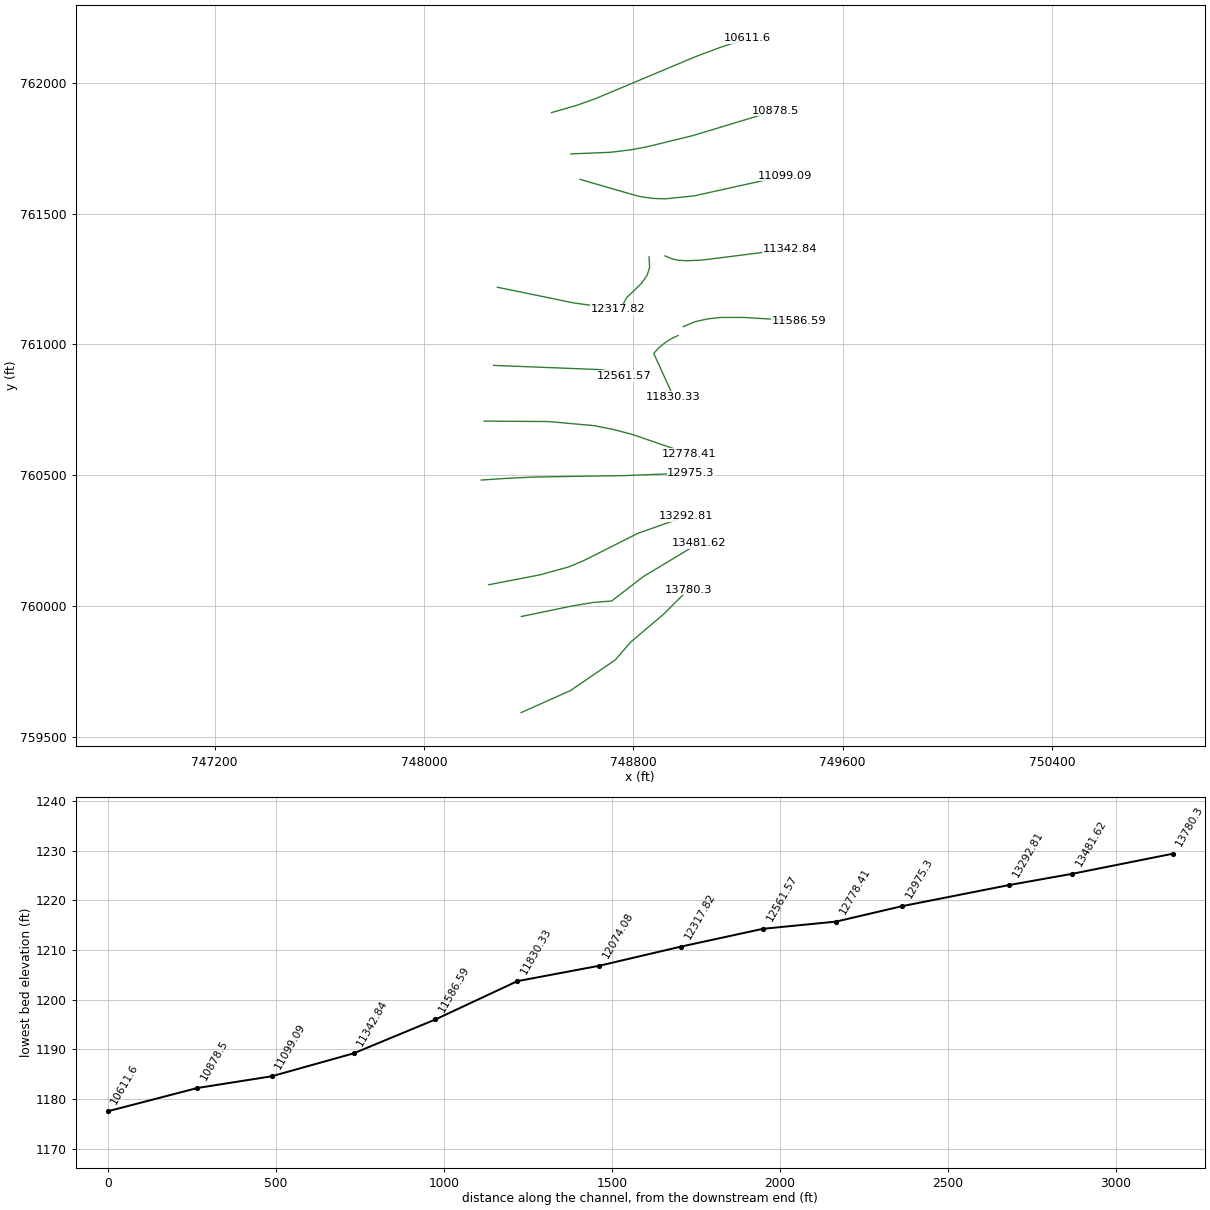
HEC-RAS study 14313_ras.prj: 14313

--- 14313_ras.g01 (geometry) --- (continued)

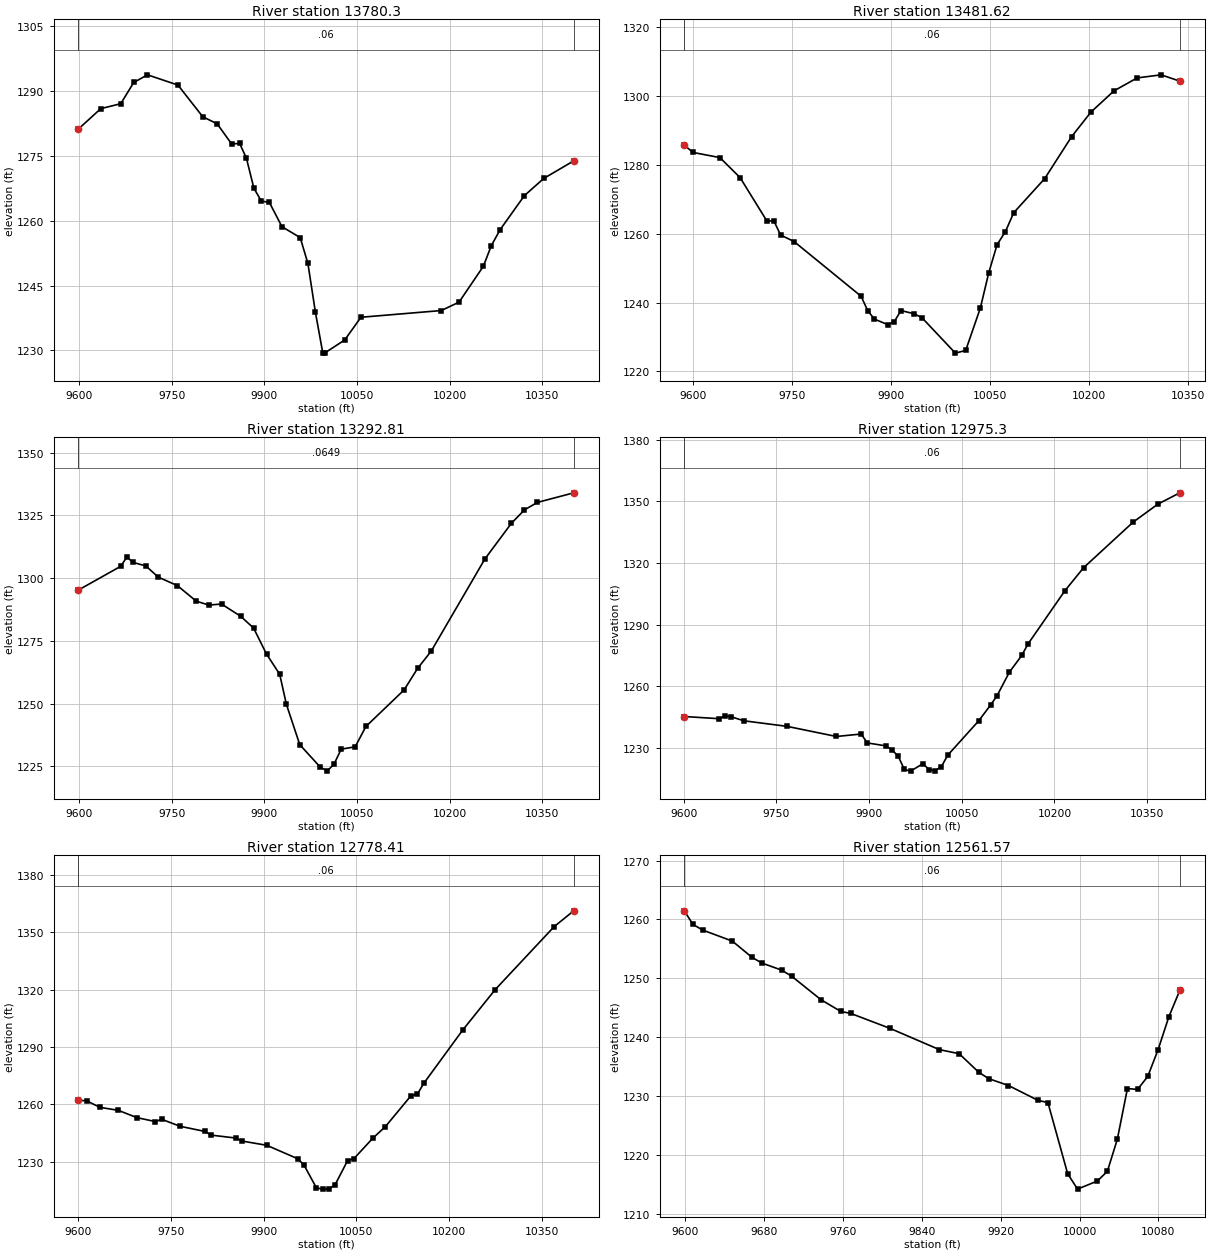
Type RM Length L Ch R = 1 , 13780.3,298.674600,298.674600,298.674600
XS GIS Cut Line= 6
748371.138805803 759592.06743081748561.095996125759676.940707459
748731.335668737759793.594768657748791.648899186759863.049128626
748915.006763677759967.333249345749009.409478929 760061.41225886
#Sta/Elev= 30
9599.0751281.2229635.4811285.9639667.7361287.0979688.7361292.0119711.0141293.785
9760.3331291.4139800.4661284.0859823.7891282.4459847.4241277.7459860.0171277.932
9871.0591274.5299883.2021267.5519895.2951264.5479908.179 1264.289928.6821258.626
9958.1341256.1189970.6221250.1439982.8391238.7889994.6761229.4499997.5561229.371
10030.261232.41810056.451237.67110186.511239.22710215.181241.16810254.471249.441
10267.561254.26910281.681257.93410320.931265.81710352.271269.79510400.851273.871
#Mann= 3 , 0 , 0
9599.075    0.06       09599.075    0.06       010400.85    0.06       0
#XS Ineff= 2 , 0
       0                               0
Bank Sta=9599.075,10400.85
Exp/Cntr=0.3,0.1

Type RM Length L Ch R = 1 ,13481.62,188.816600,188.816600,188.816600
XS GIS Cut Line= 6
748372.239989264759959.510938688748566.349789863759999.846901055
748648.245291642760013.421031699748717.594477813760018.861917207
748837.693591326760111.528614566749050.367202431760239.566809028
#Sta/Elev= 30
9586.3871285.8149599.4191283.6739640.2741282.1759670.914 1276.359711.7691263.664
9721.983 1263.849732.1961259.6759752.6231257.779 9854.231241.8799864.3661237.661
9874.4541235.2259894.5841233.6279904.6481234.5189914.7121237.7099934.7121236.779
9946.6611235.6029997.1831225.33510012.831226.12210035.08 1238.4810047.71 1248.66
10060.341256.84510072.971260.647 10085.61266.14810132.551276.06310173.281288.242
10202.581295.388 10237.61301.57410272.621305.329   10309 1306.2310337.241304.402
#Mann= 3 , 0 , 0
9586.387    0.06       09586.387    0.06       010337.24    0.06       0
#XS Ineff= 2 , 0
       0                               0
Bank Sta=9586.387,10337.24
Exp/Cntr=0.3,0.1

Type RM Length L Ch R = 1 ,13292.81,317.508700,317.508700,317.508700
XS GIS Cut Line= 6
748247.761637327760081.041465738748441.217950513760118.372290778
748553.258499305760149.040701087748610.198332937760172.818090776
748817.098593812760277.180657479 749000.93002406760342.324458074
#Sta/Elev= 30
9599.0631295.1889667.541 1304.659677.7261308.342 9687.911306.2079708.2791304.815
9728.6481300.3319759.2021297.0179789.7551290.8089810.2641289.2189830.837 1289.64
9861.8291284.7659882.7481280.0699903.6661269.7119925.0281261.6559935.8651249.654
9957.5391233.5949990.5861224.67910001.811223.05910013.151225.91610024.49  1231.8
10047.171232.74410064.611240.85610126.291255.39210148.351264.01910170.411270.922
10257.261307.63410300.211321.84510321.221327.15910342.221330.12510400.951333.944
#Mann= 3 , 0 , 0
9599.063  0.0649       09599.063  0.0649       010400.95  0.0649       0
#XS Ineff= 2 , 0
       0                               0
Bank Sta=9599.063,10400.95
Exp/Cntr=0.3,0.1

Type RM Length L Ch R = 1 , 12975.3,196.884500,196.884500,196.884500
XS GIS Cut Line= 6
748219.158353767760481.195284338748326.019629521760488.234935279
748422.413970631760492.672515462 748618.78855723 760495.91509819
748760.680783411760497.975859249 749020.56976405760508.168755229
#Sta/Elev= 30
9600.9211245.3779656.884 1244.329666.9061245.6159676.9271245.2479696.9711243.313
9767.0571240.5989847.1031235.6649887.1081236.8639897.1091232.5379927.1141231.104
9937.1151229.1539947.1161226.0789957.1181219.6339967.1191218.8229987.1221222.441
9997.1231219.56610007.121219.07910017.131221.04910027.131226.50910077.131243.166
10097.13 1251.1510107.131255.48110127.141266.95710147.141275.05810157.151280.602
 10217.21306.62910247.221317.71910327.281339.85410367.311348.61410402.911354.139
#Mann= 3 , 0 , 0
9600.921    0.06       09600.921    0.06       010402.91    0.06       0
#XS Ineff= 2 , 0
       0                               0
Bank Sta=9600.921,10402.91
Exp/Cntr=0.3,0.1

Type RM Length L Ch R = 1 ,12778.41,216.843700,216.843700,216.843700
XS GIS Cut Line= 6
748230.152730514760706.544007931748474.842534843 760704.78358428
748650.250502115760689.215243953748725.393162777 760674.14614343
 748796.68449075760655.381776226749014.869045829760580.493621749
#Sta/Elev= 30
9600.227 1262.399615.0751261.6719635.0751258.4839665.0751256.8929695.0751253.094
9725.0761251.0239735.0761252.2289765.0811248.5549805.0911245.8769815.0941243.951
9855.121 1242.429865.1411240.8479905.2191238.6329955.4151231.5949965.4751228.346
9985.5931216.3959995.6531215.70610005.711215.82110015.811217.95410036.151230.659
10046.351231.64910076.951242.34310097.351248.408 10138.71264.53310149.041265.349
10159.391271.00310222.191298.76810275.13 1320.0710370.511352.97410402.161361.224
#Mann= 3 , 0 , 0
9600.227    0.06       09600.227    0.06       010402.16    0.06       0
#XS Ineff= 2 , 0
       0                               0
Bank Sta=9600.227,10402.16
Exp/Cntr=0.3,0.1

Type RM Length L Ch R = 1 ,12561.57,243.745600,243.745600,243.745600
XS GIS Cut Line= 6
748266.332289343760919.463531039748667.985201904760903.544635516
748701.185164477760899.193781623748726.439434951760893.752565506
748745.169406431760887.865443302748764.940888986760878.847576599
#Sta/Elev= 30
 9599.011261.4679607.6841259.1739617.6911258.1999647.711 1256.339667.7241253.572
9677.7311252.6069697.7451251.4079707.7521250.3979737.7721246.3789757.785  1244.4
9767.792 1244.079807.8191241.5219857.8531237.9189877.8671237.239 9897.881234.065
9907.887    12339927.9011231.8389957.9211229.3179967.9281228.9479987.9751216.872
9998.0051214.26110018.161215.64210028.251217.27810038.391222.73910048.621231.326
10058.851231.16310069.291233.38810079.77 1237.9410090.631243.48310101.711247.958
#Mann= 3 , 0 , 0
 9599.01    0.06       0 9599.01    0.06       010101.71    0.06       0
#XS Ineff= 2 , 0
       0                               0
Bank Sta=9599.01,10101.71
Exp/Cntr=0.3,0.1

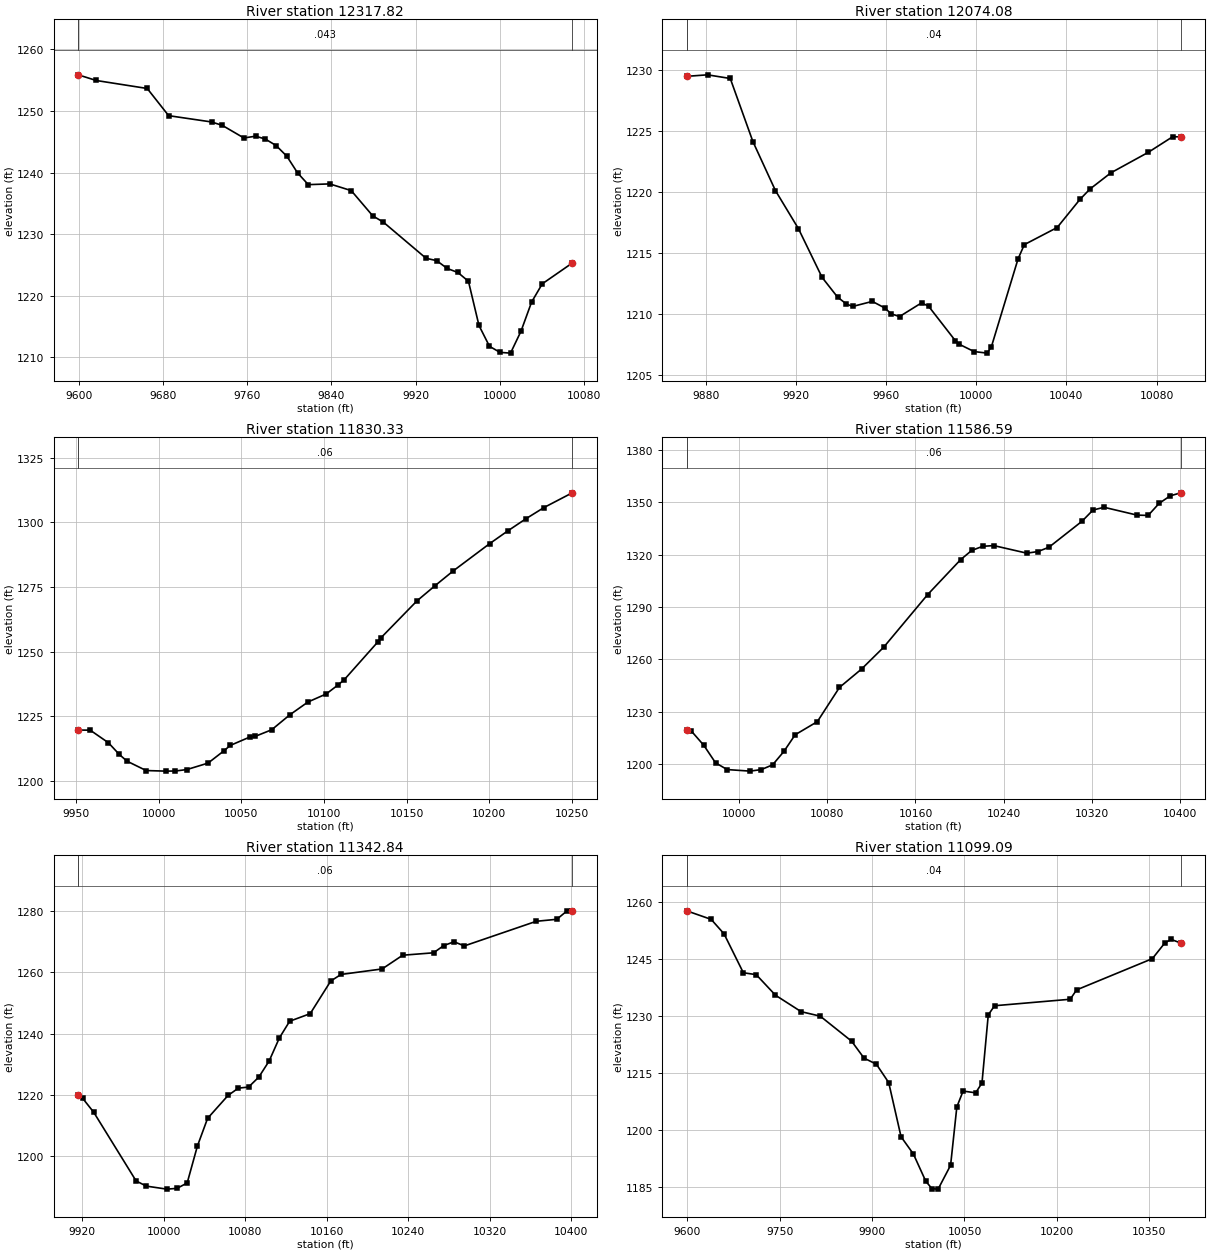
Type RM Length L Ch R = 1 ,12317.82,243.745600,243.745600,243.745600
XS GIS Cut Line= 6
748280.499261728761218.181873359748571.438817965761158.523174824
748639.603632769761148.747968987748706.037149102761145.589616465
748724.275274492761142.077339972748741.555301003761134.223944775
#Sta/Elev= 30
9599.0461255.8539616.1861254.9339664.6881253.6369685.0651249.2259725.9471248.201
9736.1671247.6459756.6081245.6089767.8511245.8919777.048 1245.439787.2691244.379
9797.4891242.6519807.7091239.941 9817.93 1238.03 9838.371238.1499858.8111237.059
9879.2521232.9679889.4721231.9269929.9571226.081 9940.061225.6949950.1621224.423
9960.2641223.7729970.3171222.3449980.3291215.173 9990.341211.78710000.351210.808
10010.361210.68410020.371214.26610030.391218.96810040.551221.93410069.081225.304
#Mann= 3 , 0 , 0
9599.046   0.043       09599.046   0.043       010069.08   0.043       0
#XS Ineff= 2 , 0
       0                               0
Bank Sta=9599.046,10069.08
Exp/Cntr=0.3,0.1

Type RM Length L Ch R = 1 ,12074.08,243.745600,243.745600,243.745600
XS GIS Cut Line= 6
748860.405868926761334.135386505748862.624259446761293.635853961
748852.444561229 761262.47019155748830.146820058761231.452518859
748774.593671891 761178.27393215748760.671117802761151.565662796
#Sta/Elev= 30
9871.4351229.5049880.6761229.6289890.7711229.328 9900.811224.1629910.8231220.142
9921.0481217.015 9931.531213.0289938.4031211.4119942.3511210.8439945.0891210.646
 9953.84 1211.069959.383 1210.529962.1751210.0459965.8971209.8179975.6981210.941
  9978.81210.6669990.7251207.8319992.4191207.548    9999 1206.9510004.791206.821
10006.711207.35610018.531214.547 10021.31215.71110035.891217.115   10046 1219.42
10050.481220.27410059.731221.59610076.241223.26710087.151224.55410090.731224.544
#Mann= 3 , 0 , 0
9871.435    0.04       09871.435    0.04       010090.73    0.04       0
#XS Ineff= 2 , 0
       0                               0
Bank Sta=9871.435,10090.73
Exp/Cntr=0.3,0.1

Type RM Length L Ch R = 1 ,11830.33,243.745700,243.745700,243.745700
XS GIS Cut Line= 6
 748971.55801186761033.733558923748949.061393946761023.269708633
748925.952661544761009.381656498748897.418025821760986.629662842
748878.437815964760965.078794584748953.796021879760799.462642357
#Sta/Elev= 30
9951.3281219.6029958.5611219.573 9969.591214.7019976.1391210.1959980.847 1207.57
9992.4391203.94110004.331203.71710010.141203.76110017.121204.33110029.91 1206.83
 10039.61211.63110043.261213.644 10055.11216.89610058.391217.16510068.411219.729
10079.391225.52210090.381230.48110101.371233.58110108.311236.94610112.351239.134
10132.461253.59810134.331255.192 10156.31269.60310167.291275.50510178.271281.211
10200.251291.73710211.23 1296.6710222.221301.38110233.211305.74210250.281311.424
#Mann= 3 , 0 , 0
9951.328    0.06       09951.328    0.06       010250.28    0.06       0
#XS Ineff= 2 , 0
       0                               0
Bank Sta=9951.328,10250.28
Exp/Cntr=0.3,0.1

Type RM Length L Ch R = 1 ,11586.59,243.745600,243.745600,243.745600
XS GIS Cut Line= 6
748991.545531523761067.968081397749038.490373241761087.057921632
749087.571870536761097.673284748749135.087862446761102.705002754
749220.998016107 761102.73375632749434.524861068761089.926339417
#Sta/Elev= 30
9952.1791219.6289956.1761219.1089967.7481210.7629978.3841200.7529988.9471196.901
10009.771196.008   100201196.90110030.231199.61710040.461207.27710050.691216.822
10070.851224.34910090.961243.94510111.021254.46710131.031266.89410171.04 1297.08
10201.07 1317.1310211.081322.372 10221.11324.73710231.121325.15210261.171320.808
10271.191321.73110281.211324.19110311.261339.07310321.281345.505 10331.3 1347.09
10361.351342.59410371.371342.42510381.39 1349.3510391.411353.62810400.951355.363
#Mann= 3 , 0 , 0
9952.179    0.06       09952.179    0.06       010400.95    0.06       0
#XS Ineff= 2 , 0
       0                               0
Bank Sta=9952.179,10400.95
Exp/Cntr=0.3,0.1

Type RM Length L Ch R = 1 ,11342.84,243.745600,243.745600,243.745600
XS GIS Cut Line= 6
748921.195489084761338.077637096748952.232797165761325.345146828
748973.200049693761321.353094966749002.792869832761319.285370788
749062.298020855761321.906917487749400.024619218761364.438496009
#Sta/Elev= 30
9916.3591219.8619920.8341218.8069931.5391214.3049973.1361191.8499983.165 1190.16
10003.211189.17510013.221189.41910023.231191.19210033.241203.24510043.251212.312
10063.291219.79110073.371222.18610083.441222.54610093.521225.815 10103.61231.053
10113.68 1238.6210123.761244.06310143.921246.54410164.081257.21910174.161259.361
10214.471261.15910234.631265.64510264.871266.43610274.941268.80310285.021270.042
 10295.11268.68910365.661276.73710385.81 1277.3910395.891280.15910400.961279.982
#Mann= 3 , 0 , 0
9916.359    0.06       09916.359    0.06       010400.96    0.06       0
#XS Ineff= 2 , 0
       0                               0
Bank Sta=9916.359,10400.96
Exp/Cntr=0.3,0.1

Type RM Length L Ch R = 1 ,11099.09,220.596300,220.596300,220.596300
XS GIS Cut Line= 6
748596.955058519761630.483365667748818.482536867761566.254989827
748871.454883706761557.854799842748921.750576407761556.021499108
749032.077858966 761567.27668138749379.904148713761644.167367372
#Sta/Elev= 30
9599.0981257.7539638.8191255.504  9659.71251.6999691.0221241.4689711.9031240.969
9743.2251235.5569784.867 1231.239815.8541230.0519866.7531223.4739886.9611219.012
9906.9751217.4159926.9881212.5839947.0241198.3349967.0711193.7949987.1181186.651
9997.1421184.68810007.181184.56110027.441190.83510037.581206.18410047.73 1210.35
10068.16 1209.8910078.381212.47410088.591230.38510098.811232.79210221.641234.499
 10231.91236.95310354.941245.17510375.451249.356 10385.71250.22610400.981249.278
#Mann= 3 , 0 , 0
9599.098    0.04       09599.098    0.04       010400.98    0.04       0
#XS Ineff= 2 , 0
       0                               0
Bank Sta=9599.098,10400.98
Exp/Cntr=0.3,0.1

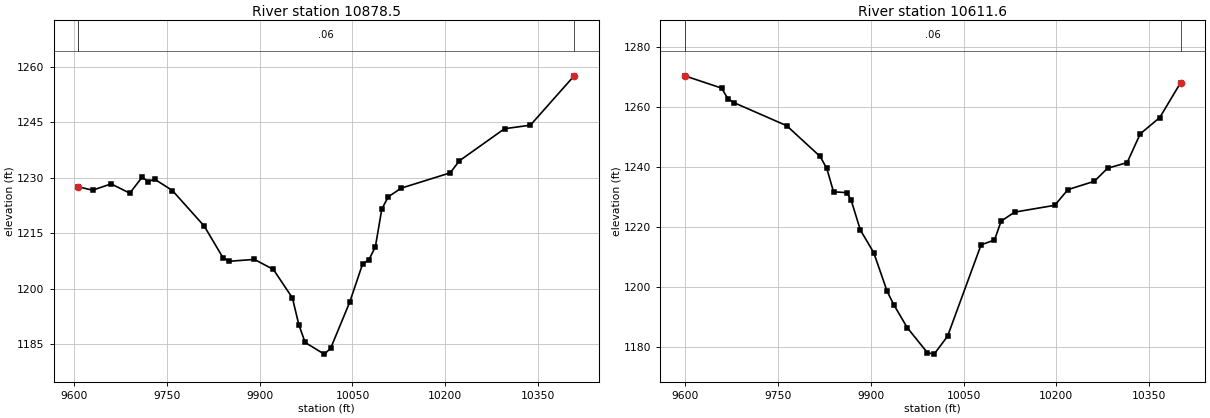
Type RM Length L Ch R = 1 , 10878.5,266.894900,266.894900,266.894900
XS GIS Cut Line= 6
748561.862603308761727.793954058748713.840224097761734.068433076
748791.804541326761743.656311694 748854.86416984761755.524904451
749026.487152768761797.438674317749342.800154666761892.948753262
#Sta/Elev= 30
9606.6171227.567 9629.761226.6519659.7671228.3619689.7931225.8429709.8271230.172
9719.8441228.9919729.861 1229.649758.7511226.5639810.2961216.9069840.554 1208.36
 9850.731207.3859891.4321207.8869922.1351205.1579952.9231197.4289963.1861190.224
9973.4491185.37310004.261182.21110014.591183.739 10045.61196.31610066.281206.605
10076.621207.80110087.051211.29310097.491221.55810107.941224.85610128.831227.203
 10208.11231.34710222.841234.59910295.971243.31410337.751244.26610408.571257.649
#Mann= 3 , 0 , 0
9606.617    0.06       09606.617    0.06       010408.57    0.06       0
#XS Ineff= 2 , 0
       0                               0
Bank Sta=9606.617,10408.57
Exp/Cntr=0.3,0.1

Type RM Length L Ch R = 1 , 10611.6,243.745700,243.745700,243.745700
XS GIS Cut Line= 6
748487.813155544761885.723594561748583.967767751761913.468394617
748654.252557354761938.398009741 749038.84717489762099.849768802
749133.691778451762135.344049003749237.037457397762169.726463925
#Sta/Elev= 30
9599.0371270.2689658.557 1266.179668.9651262.5649679.3721261.2579763.872 1253.64
9817.8891243.4049828.7361239.3849839.5831231.6279861.2781231.323 9868.161228.789
9882.9721218.8729904.6671211.3279926.3611198.4089937.2081193.9379958.9031186.301
9991.444    117810002.311177.51710023.991183.461 10078.21213.93410099.891215.554
10110.731221.84710132.421224.84510197.371227.10910218.721232.34210261.431235.123
10282.791239.46110314.521241.354 10335.61250.92510367.221256.36310400.981267.979
#Mann= 3 , 0 , 0
9599.037    0.06       09599.037    0.06       010400.98    0.06       0
#XS Ineff= 2 , 0
       0                               0
Bank Sta=9599.037,10400.98
Exp/Cntr=0.3,0.1