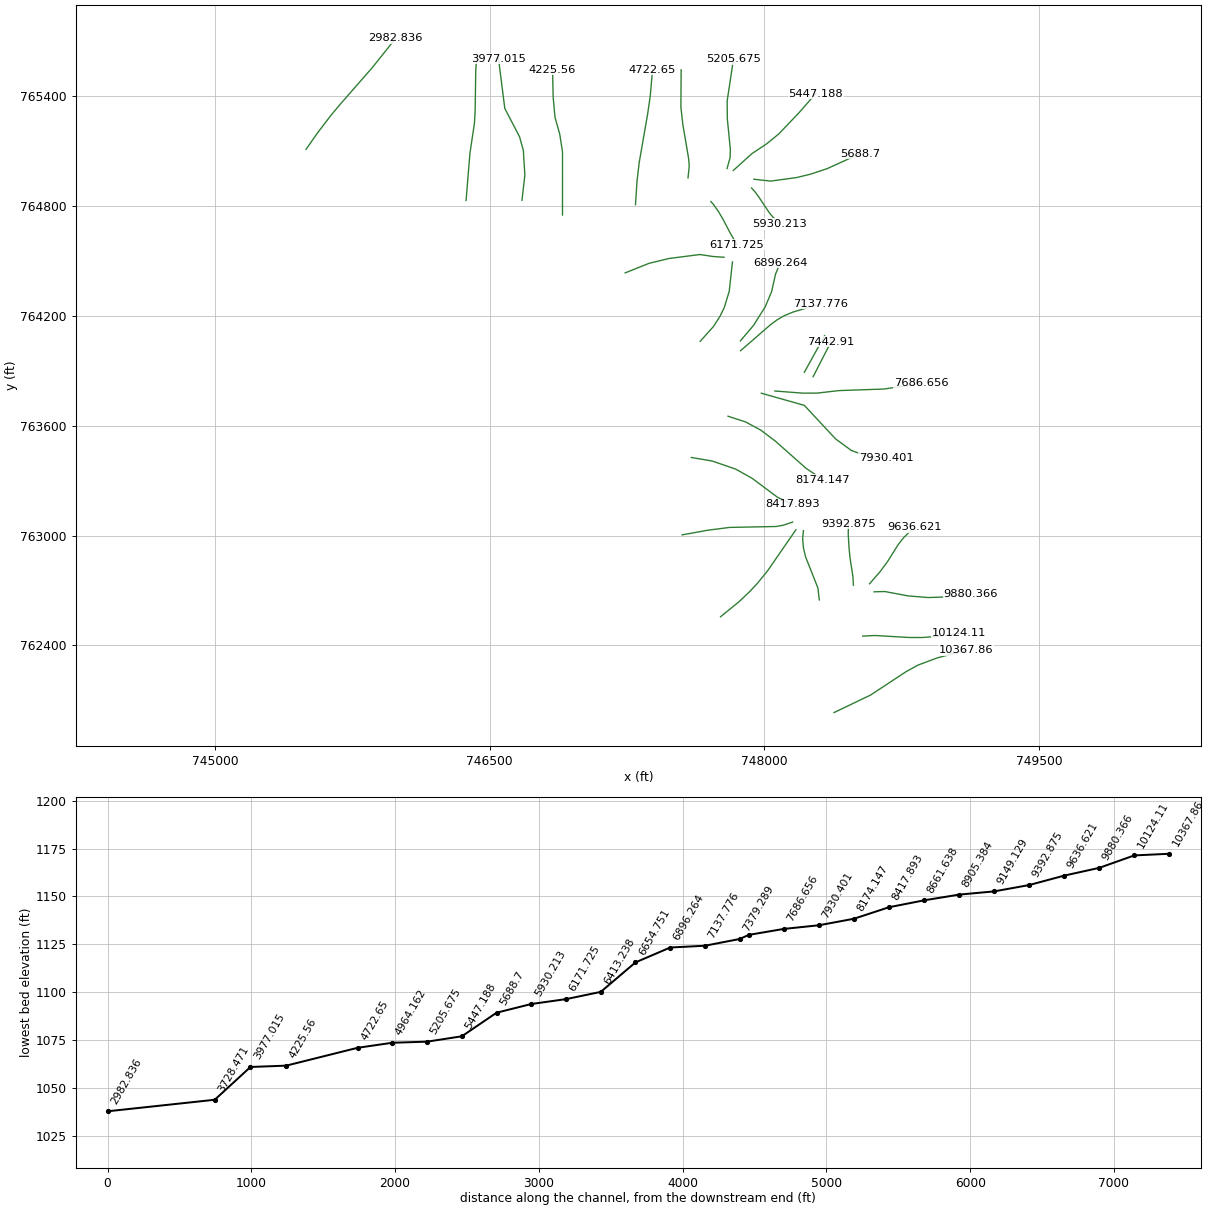
HEC-RAS study 14313_ras.prj: 14313

--- 14313_ras.g01 (geometry) --- (continued)

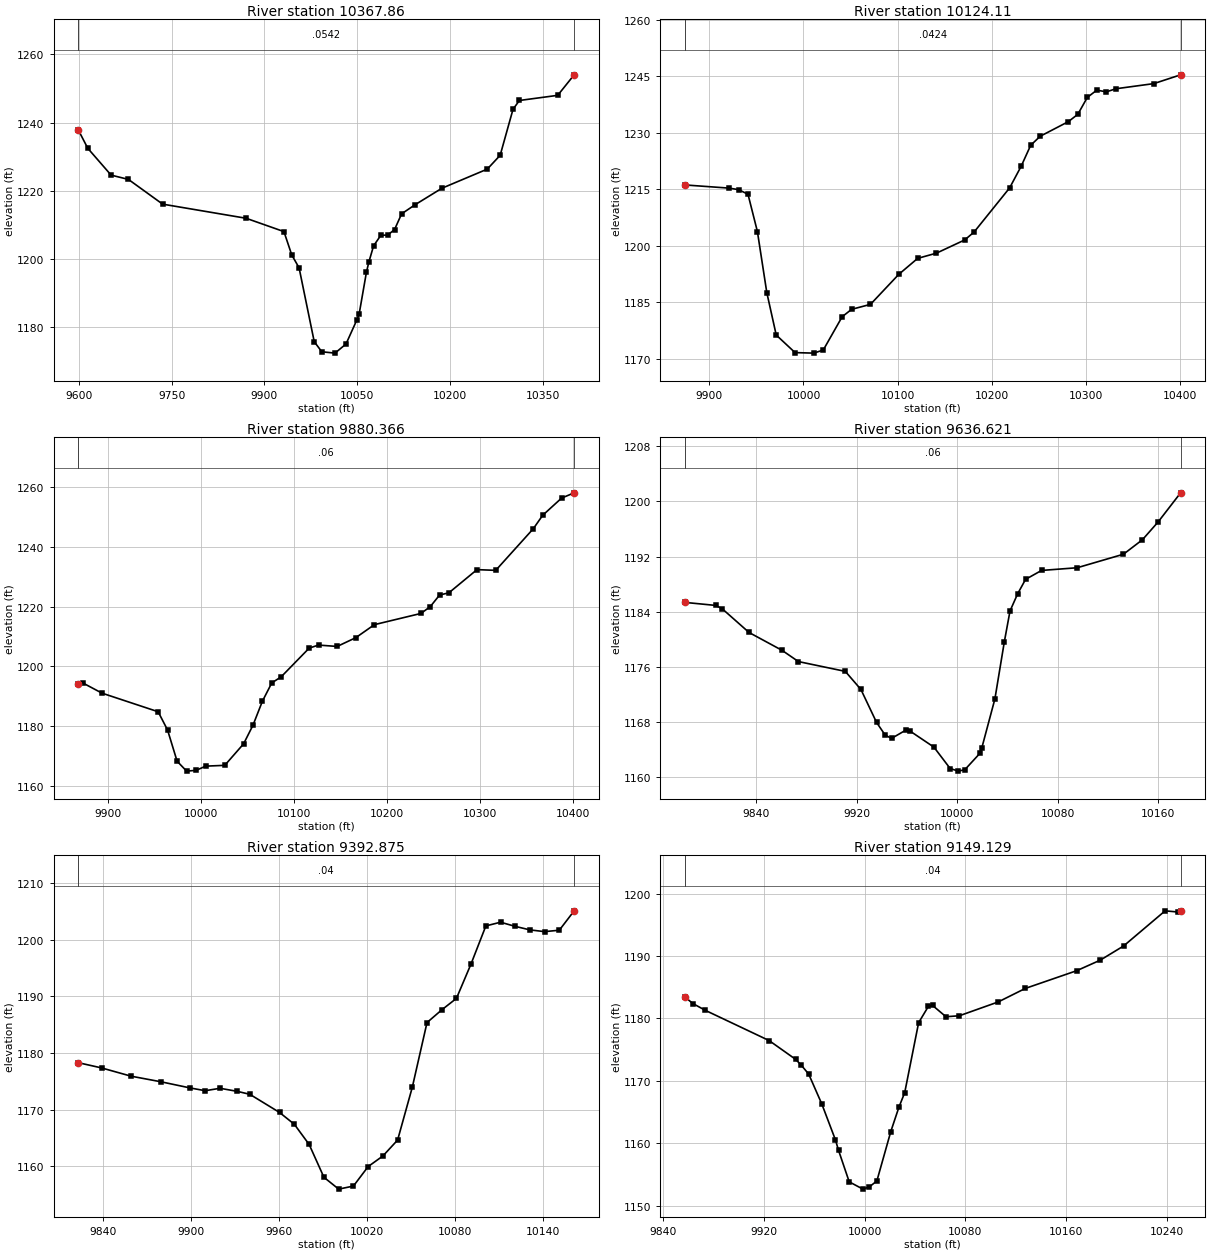
Type RM Length L Ch R = 1 ,10367.86,243.745600,243.745600,243.745600
XS GIS Cut Line= 6
748381.036624791762033.417539485748580.575750204 762129.04596848
748776.291472771762257.809185572748840.201145367762292.852558169
748942.700112218762331.332842041 749100.79983936762373.591618955
#Sta/Elev= 30
9599.0681237.8189614.3571232.4499652.0451224.5819680.0561223.3199735.4371216.059
9870.4311211.9149931.6021208.0019944.2931201.1239956.0921197.3689980.5811175.693
9992.8261172.74110014.17 1172.3410031.991175.02210049.811182.20210053.251183.854
10064.95 1196.0310068.851199.03610076.591203.82810088.221206.90410099.441206.997
10110.471208.597 10121.91213.22110143.761215.89410186.961220.71810260.481226.345
10281.291230.40110302.091243.91710312.411246.48310374.331247.98910400.95 1254.01
#Mann= 3 , 0 , 0
9599.068  0.0542       09599.068  0.0542       010400.95  0.0542       0
#XS Ineff= 2 , 0
       0                               0
Bank Sta=9599.068,10400.95
Exp/Cntr=0.3,0.1

Type RM Length L Ch R = 1 ,10124.11,243.745600,243.745600,243.745600
XS GIS Cut Line= 6
748537.961512459762451.083420096748603.726294925762454.436622494
748791.227753715762443.544259062748860.732395069762443.368510166
748955.208165155762450.386461896749063.240101147762465.451333618
#Sta/Elev= 30
9873.8331216.1159921.0091215.2699931.0111214.8659941.0141213.6439951.0191203.736
9961.0241187.5239971.0281176.2779991.0371171.61610011.051171.47710021.061172.312
10041.121181.13410051.151183.10110071.211184.41810101.311192.38310121.371196.623
10141.391198.01510171.391201.51510181.391203.62210219.141215.32710231.481221.109
10241.511226.62910251.54 1229.0210281.62 1232.9210291.651234.86610301.741239.343
10311.841241.28310321.941240.81410332.031241.63910372.421243.00710400.931245.339
#Mann= 3 , 0 , 0
9873.833  0.0424       09873.833  0.0424       010400.93  0.0424       0
#XS Ineff= 2 , 0
       0                               0
Bank Sta=9873.833,10400.93
Exp/Cntr=0.3,0.1

Type RM Length L Ch R = 1 ,9880.366,243.745600,243.745600,243.745600
XS GIS Cut Line= 6
748599.708715026762693.077347916748658.656716573762694.636855921
748786.357172043762670.743427587748895.211243418762661.781655882
748996.804079637762665.155713703749128.368234424762682.889496387
#Sta/Elev= 30
9868.0581194.1339873.3861194.3799893.5281191.0489953.8391184.8329963.9681178.722
9974.2121168.2819984.4561164.972  9994.7 1165.2410004.961166.64210025.431166.904
 10045.71174.10910055.841180.38210065.911188.37110075.971194.47510086.041196.505
 10116.21206.12110126.211207.12910146.241206.67210166.271209.60610186.27 1213.96
10236.311217.71310246.331219.99610256.341223.86710266.361224.61610296.541232.363
10316.67 1232.1210357.041246.04310367.161250.54210387.421256.28110400.96 1258.05
#Mann= 3 , 0 , 0
9868.058    0.06       09868.058    0.06       010400.96    0.06       0
#XS Ineff= 2 , 0
       0                               0
Bank Sta=9868.058,10400.96
Exp/Cntr=0.3,0.1

Type RM Length L Ch R = 1 ,9636.621,243.745600,243.745600,243.745600
XS GIS Cut Line= 6
748574.924718074 762736.70849164748633.173882191762803.610835878
748673.493253734762858.157729085748730.892714057 762950.05292279
748760.142898642762987.330741985748818.127983871763045.676718378
#Sta/Elev= 30
9783.1281185.3679807.8391184.9269812.9921184.4299834.2541181.0079860.5311178.418
9873.5721176.7899910.8781175.3689923.3141172.7429935.7491167.971  9942.61166.135
 9947.661165.6529959.3281166.8829962.0061166.7659981.4121164.3899994.3331161.289
10000.831160.91110006.021161.11810017.911163.47210019.46 1164.2310029.941171.376
10037.451179.65810041.971184.12510048.051186.61310054.341188.70310067.051189.997
10095.431190.38910132.251192.34710147.381194.45210159.851197.02710177.761201.247
#Mann= 3 , 0 , 0
9783.128    0.06       09783.128    0.06       010177.76    0.06       0
#XS Ineff= 2 , 0
       0                               0
Bank Sta=9783.128,10177.76
Exp/Cntr=0.3,0.1

Type RM Length L Ch R = 1 ,9392.875,243.745700,243.745700,243.745700
XS GIS Cut Line= 6
748486.904547307762729.181593957748484.320380694 762777.41737268
748468.480483425762878.185393437 748463.12212477762932.747063385
748458.590805518763007.741616885748459.936705892763065.105684363
#Sta/Elev= 30
9823.4551178.2939839.2741177.3729859.3481175.9169879.5071174.9389899.7521173.831
9909.8751173.3519919.9981173.7789931.8521173.2299940.243 1172.729960.4891169.518
9970.612 1167.42 9980.691163.8629990.7481158.075 10000.81155.98410010.841156.525
10020.881159.96510030.921161.83410040.941164.64410050.961173.97710060.971185.377
10070.99 1187.6110081.011189.64110091.031195.76610101.051202.42810111.051203.083
10121.051202.34910131.051201.72910141.06 1201.4210151.08 1201.67 10161.21205.092
#Mann= 3 , 0 , 0
9823.455    0.04       09823.455    0.04       0 10161.2    0.04       0
#XS Ineff= 2 , 0
       0                               0
Bank Sta=9823.455,10161.2
Exp/Cntr=0.3,0.1

Type RM Length L Ch R = 1 ,9149.129,243.745600,243.745600,243.745600
XS GIS Cut Line= 6
 748300.67526678762648.586594441748292.790525237762714.665527362
748225.677836478762884.037282777748214.347720471762931.459534503
748209.626700305762982.127898636 748213.90319056 763027.15023309
#Sta/Elev= 30
9856.9681183.4499863.3851182.386 9873.391181.2879923.9791176.4589944.9581173.464
9949.4231172.5459955.4481171.0859965.9381166.2669976.7321160.5349979.1731158.874
9987.6541153.8299998.5751152.66310003.751153.03610009.631153.97510020.69 1161.88
10027.141165.77710031.761168.11410042.821179.32110050.531181.91710053.881182.089
10064.561180.27310075.191180.42910106.081182.64410127.64 1184.8110168.481187.648
10187.151189.33210205.771191.60910238.761197.23610248.851197.04710251.071197.213
#Mann= 3 , 0 , 0
9856.968    0.04       09856.968    0.04       010251.07    0.04       0
#XS Ineff= 2 , 0
       0                               0
Bank Sta=9856.968,10251.07
Exp/Cntr=0.3,0.1

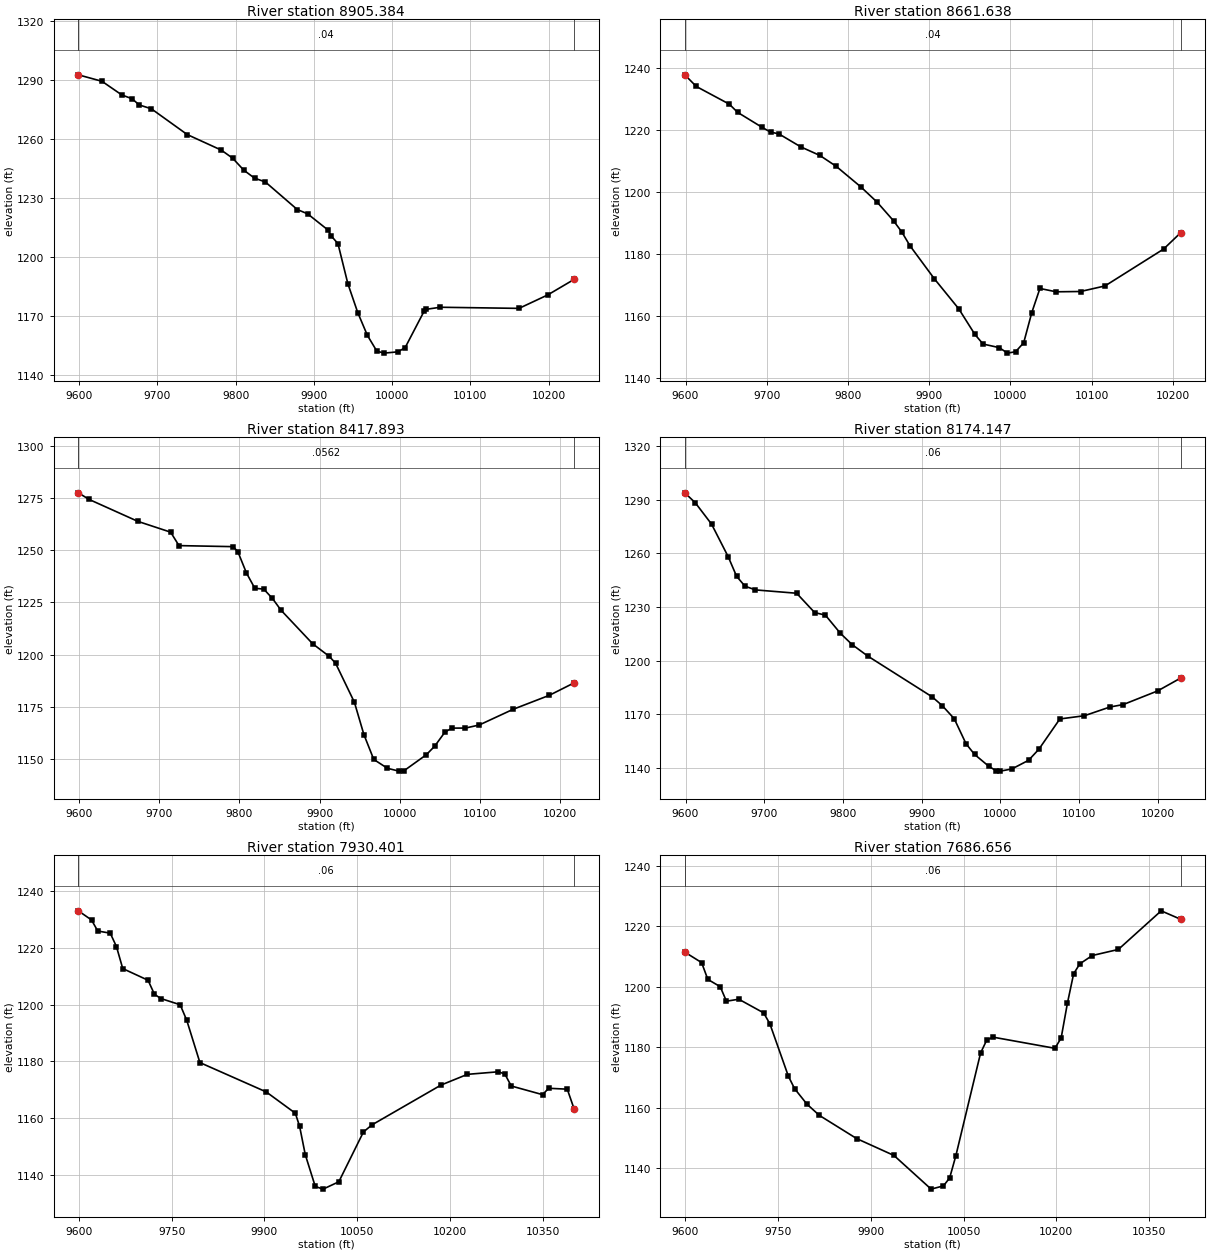
Type RM Length L Ch R = 1 ,8905.384,243.745600,243.745600,243.745600
XS GIS Cut Line= 6
747761.058507689762556.639845041747863.027392247762639.770303901
747918.897903787762692.992745804747963.654137838 762740.75003438
748018.589145546762808.532103107748173.142156474 763032.42105646
#Sta/Elev= 30
9599.043 1292.659629.2441289.3629654.5841282.4149667.6911280.4729676.8541277.323
9692.3231275.3659738.2221262.2389781.7171254.3289796.2151250.2169810.5541244.083
9824.2591240.0389837.9641238.1319878.8381224.0669891.9741221.903 9918.171213.613
 9921.921210.7629930.8021206.7079943.4341186.3459956.0661171.642 9968.361160.047
9980.4671151.9969989.6351150.98110007.531151.64110016.66  1153.810040.721172.197
10043.511173.27710061.511174.33510162.14 1173.7610198.861180.61310232.61 1188.53
#Mann= 3 , 0 , 0
9599.043    0.04       09599.043    0.04       010232.61    0.04       0
#XS Ineff= 2 , 0
       0                               0
Bank Sta=9599.043,10232.61
Exp/Cntr=0.3,0.1

Type RM Length L Ch R = 1 ,8661.638,243.745600,243.745600,243.745600
XS GIS Cut Line= 6
747551.043099335763004.100733315747691.707320031763029.576314566
747811.175251868763044.860196521748065.021982922763049.910585847
748102.658785344763056.776090308748154.775390855763073.876677021
#Sta/Elev= 30
9599.0611237.7459613.2451233.9899653.8961228.2849664.0591225.6549694.5471220.762
9704.7091219.2719714.8721218.7069742.0141214.4959765.4961211.7329785.6591208.208
9815.9041201.5949836.0671196.642 9856.231190.6349866.286 1187.079876.3021182.645
9906.3491171.9819936.3961162.3039956.4111153.9939966.4131150.9119986.418 1149.75
 9996.421147.98110006.421148.42910016.421151.30810026.431161.07410036.431168.838
10056.431167.76110086.461167.85710116.571169.65210188.781181.55410209.731186.794
#Mann= 3 , 0 , 0
9599.061    0.04       09599.061    0.04       010209.73    0.04       0
#XS Ineff= 2 , 0
       0                               0
Bank Sta=9599.061,10209.73
Exp/Cntr=0.3,0.1

Type RM Length L Ch R = 1 ,8417.893,243.745600,243.745600,243.745600
XS GIS Cut Line= 6
747601.573874642763426.901757369747716.124346242 763407.40736917
747843.513486483763363.525180365747933.267715689763313.441127288
748073.400138756763208.751559613748153.861743831763170.274398959
#Sta/Elev= 30
9599.1011277.3949612.6451274.218 9673.37 1263.759714.2261258.5919724.6271252.167
9792.1821251.6689798.0391249.2969808.8021239.0579819.2241231.7679830.3281231.389
9841.0911226.964 9851.921221.2859891.2481205.2919912.1541199.1979919.8891195.989
9943.4071177.3029955.2651161.8479967.5631149.9659984.6611145.728    99991144.381
10005.151144.52910033.021152.18410043.571156.30510056.381163.05110065.03 1164.94
10081.871164.96310099.071166.42410141.291173.91710186.541180.618 10217.51186.574
#Mann= 3 , 0 , 0
9599.101  0.0562       09599.101  0.0562       0 10217.5  0.0562       0
#XS Ineff= 2 , 0
       0                               0
Bank Sta=9599.101,10217.5
Exp/Cntr=0.3,0.1

Type RM Length L Ch R = 1 ,8174.147,243.745700,243.745700,243.745700
XS GIS Cut Line= 6
747802.095057105763652.221238038747897.359791106763621.433769553
747980.937704555763576.464154804748060.403293384763516.401960149
748226.964058325763368.729746144748320.062866925763306.026895271
#Sta/Elev= 30
9599.0731293.8039612.408 1288.259633.076 1276.329654.2471258.083 9664.881247.184
9675.513 1241.669688.7951239.5829741.182 1237.719764.0261226.9359777.7061225.475
9796.816 1215.319811.5191209.0829831.4051202.6629913.4141179.8199926.2811174.895
9941.3911167.6369956.4211153.6329967.1881147.7049985.4641141.002 9994.771138.545
9999.9941138.35810014.641139.57810035.871144.41510048.981150.61410075.581167.499
10106.821169.30610139.221174.17210155.991175.51610199.831183.16310229.031190.325
#Mann= 3 , 0 , 0
9599.073    0.06       09599.073    0.06       010229.03    0.06       0
#XS Ineff= 2 , 0
       0                               0
Bank Sta=9599.073,10229.03
Exp/Cntr=0.3,0.1

Type RM Length L Ch R = 1 ,7930.401,243.745600,243.745600,243.745600
XS GIS Cut Line= 6
 747983.90450561 763777.99264111748218.781981039763711.698644301
748388.760642372763529.095333818748474.977299343763465.696382073
748562.453391516763432.830204472748666.135159833763424.282645038
#Sta/Elev= 30
9599.1071233.0289620.4051229.8129630.5021225.9169650.6941225.1579660.7911220.403
9670.9031212.6829711.8231208.5649722.1441203.6419732.4651202.1279763.7761199.931
9774.3911194.4589795.671 1179.55 9902.961169.2069949.9511161.7069956.9121157.078
9966.012 1147.139982.1911135.9049994.8311134.95310020.281137.539 10060.11155.096
 10073.81157.58510185.431171.61510228.221175.40410278.261176.30510288.721175.526
 10299.11171.29910349.651168.25310359.681170.49210389.681170.17710400.821163.174
#Mann= 3 , 0 , 0
9599.107    0.06       09599.107    0.06       010400.82    0.06       0
#XS Ineff= 2 , 0
       0                               0
Bank Sta=9599.107,10400.82
Exp/Cntr=0.3,0.1

Type RM Length L Ch R = 1 ,7686.656,243.745600,243.745600,243.745600
XS GIS Cut Line= 6
748057.876420256763789.971285752748209.579076318 763778.49796661
748288.112620715763778.542676644748407.525226989 763792.30390378
748653.973323049763800.875475604748855.956445731763831.177601999
#Sta/Elev= 30
9599.068 1211.389626.269 1207.919636.2971202.3659656.3541199.9489666.3831195.155
 9686.441195.8069726.554  1191.39736.5831187.7179766.6291170.3389776.6311166.246
9796.6371161.1289816.6461157.4259876.9621149.7559937.3591144.1689997.4521133.044
10017.451134.12510027.451136.76210037.45 1144.0910077.461178.04910087.46 1182.33
10097.471183.27710197.681179.58710207.751183.01410217.831194.452 10227.91204.207
10237.981207.51410258.131210.25510300.221212.25710369.521225.02210400.961222.235
#Mann= 3 , 0 , 0
9599.068    0.06       09599.068    0.06       010400.96    0.06       0
#XS Ineff= 2 , 0
       0                               0
Bank Sta=9599.068,10400.96
Exp/Cntr=0.3,0.1

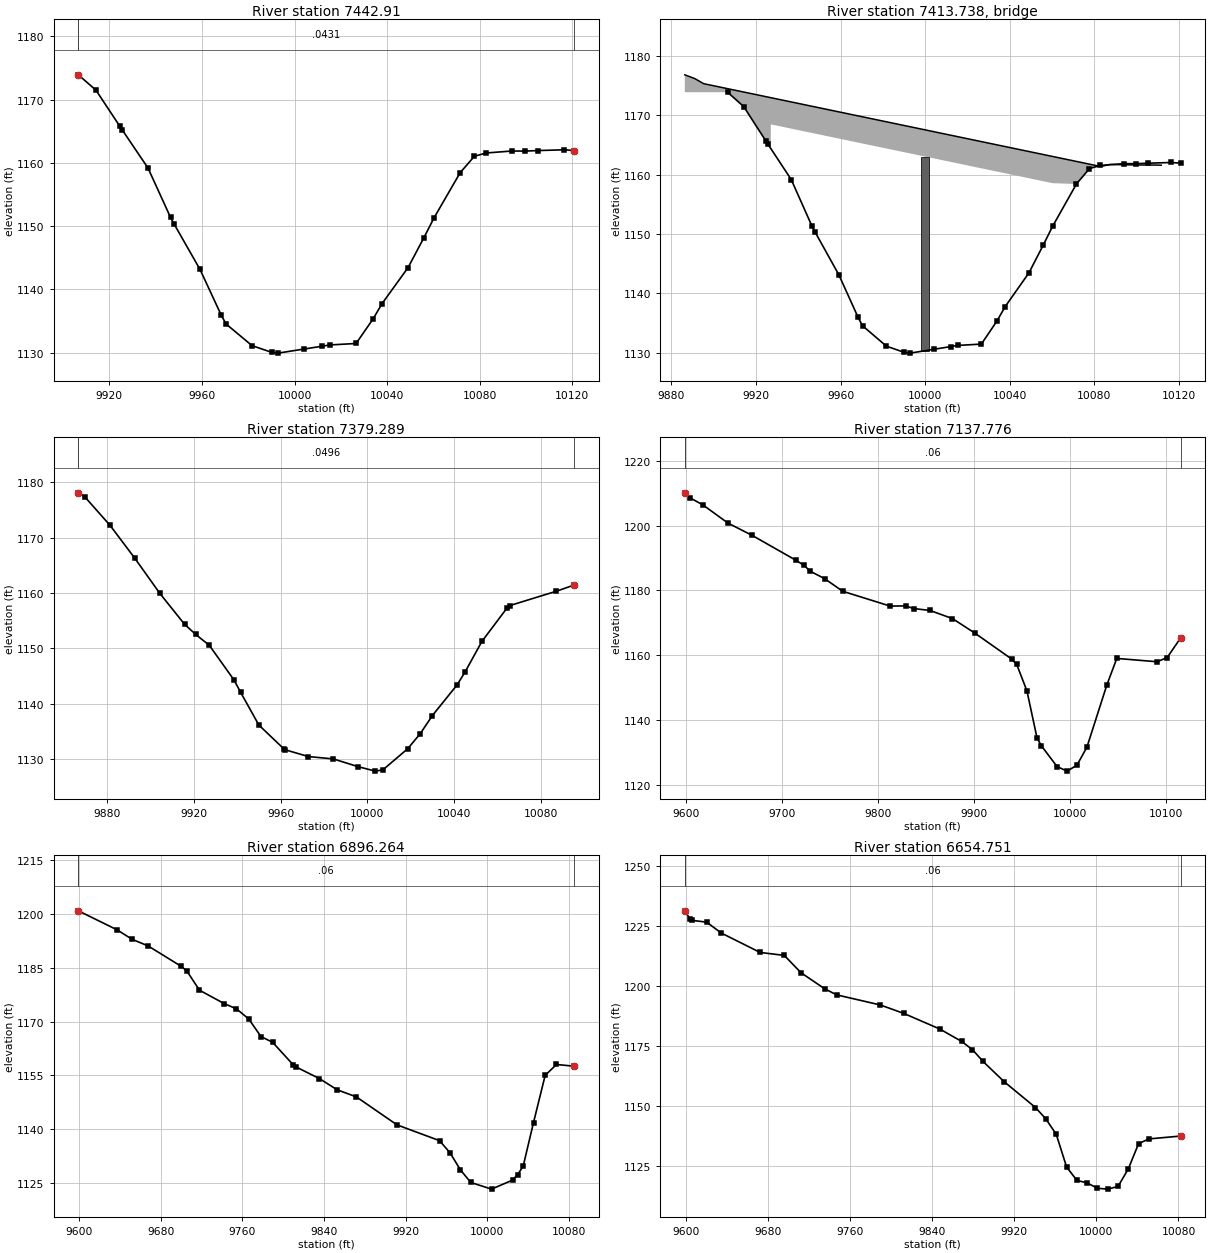
Type RM Length L Ch R = 1 , 7442.91,63.621400,63.621400,63.621400
XS GIS Cut Line= 2
748266.782759577763868.214662865748364.699426264 764058.83966288
#Sta/Elev= 30
9906.564  1173.99914.1921171.4719924.5491165.7469925.4351165.2569936.6771159.172
9946.4351151.3589947.9191150.3549959.1611143.1489968.3211135.9369970.4031134.538
9981.6451131.1129990.2071130.0459992.8871129.92910004.131130.57710012.091131.027
10015.371131.22510026.611131.45210033.981135.34410037.861137.761 10049.11143.453
10055.87 1148.1310060.341151.32410071.581158.42910077.751161.03310082.821161.552
10094.071161.86510099.641161.84810105.311161.93510116.551162.05610120.871161.943
#Mann= 3 , 0 , 0
9906.564  0.0431       09906.564  0.0431       010120.87  0.0431       0
#XS Ineff= 2 , 0
       0                               0
Bank Sta=9906.564,10120.87
Exp/Cntr=0.3,0.1

Type RM Length L Ch R = 3 ,7413.738,,,
BEGIN DESCRIPTION:
END DESCRIPTION:
Bridge Culvert--1,0,-1,-1, 0
Deck Dist Width WeirC Skew NumUp NumDn MinLoCord MaxHiCord MaxSubmerge Is_Ogee
16.554800,30.511800,2.6,0, 14, 14, , , 0.95, 0, 0,0,,
 9886.31 9891.07 9895.24 9927.00 9927.0010073.0010073.0010083.0310087.5110087.84
10098.9610110.0810110.3810111.69
 1176.83 1176.19 1175.34 1172.98 1172.98 1162.13 1162.13 1161.38 1161.73 1161.72
 1161.64 1161.62 1161.61 1161.60
  176.83  176.19  175.34  172.98 1168.48 1157.63  162.13  161.38  161.73  161.72
  161.64  161.62  161.61  161.60
 9886.31 9891.07 9895.24 9927.00 9927.0010073.0010073.0010083.0310087.5110087.84
10098.9610110.0810110.3810111.69
 1176.83 1176.19 1175.34 1172.98 1172.98 1162.13 1162.13 1161.38 1161.73 1161.72
 1161.64 1161.62 1161.61 1161.60
  176.83  176.19  175.34  172.98 1168.48 1157.63  162.13  161.38  161.73  161.72
  161.64  161.62  161.61  161.60
Pier Skew, UpSta & Num, DnSta & Num=  ,10000.00, 2 ,10000.00, 2 , 0 , 0 , 0 ,,
    4.00    4.00
  167.55 1167.55
    4.00    4.00
  167.55 1167.55
BR Coef=-1 , 0 , 0 ,, 0 ,,,0.8,0,1,0,
WSPro=,,,, 1 ,,,, 0 ,,,, 0 ,,,,-1 ,-1 ,-1 , 0 , 0 , 0 , 0 , 0
BC Design=,, 0 ,, 0 ,,,,,,

Type RM Length L Ch R = 1 ,7379.289,241.512700,241.512700,241.512700
XS GIS Cut Line= 2
 748218.86609292763892.172996208748329.282759577764092.172996193
#Sta/Elev= 28
9866.8361178.0949870.0651177.2579881.4881172.1949892.9111166.2389904.3331159.939
9915.7561154.3369920.9081152.4939927.1791150.5259938.6021144.2329941.5981142.034
9950.024  1136.19961.4471131.8319962.2881131.616 9972.871130.4059984.2931129.982
9995.7151128.58510003.671127.77310007.141127.99410018.56 1131.8110024.361134.537
10029.98 1137.8310041.411143.39410045.05 1145.7310052.831151.24810064.251157.214
10065.74 1157.72 10087.11160.30210095.291161.429
#Mann= 3 , 0 , 0
9866.836  0.0496       09866.836  0.0496       010095.29  0.0496       0
#XS Ineff= 2 , 0
       0                               0
Bank Sta=9866.836,10095.29
Exp/Cntr=0.3,0.1

Type RM Length L Ch R = 1 ,7137.776,241.512600,241.512600,241.512600
XS GIS Cut Line= 6
747870.463257823764010.117104485748031.822236828764150.281643627
748068.859853417764178.058601465748106.959505088764200.706158552
748157.793772807 764221.64001686748308.307530134764266.454718597
#Sta/Elev= 30
9599.0821210.0969604.9831208.4759617.992 1206.36 9644.011200.7689669.4051196.942
9714.4681189.3569723.515 1187.689729.5371185.9419744.6061183.6459763.6181179.723
9812.8411175.1729829.313 1175.219837.372  1174.49854.3121173.8229877.9131171.305
 9901.18 1166.83 9939.431158.8599944.8291157.1699955.4981148.9769965.9811134.482
9970.5661132.0499986.8011125.6769997.211 1124.2510007.58 1126.0810017.95 1131.63
 10038.71150.80710049.071159.01610090.99 1157.9910101.531159.27710115.571165.333
#Mann= 3 , 0 , 0
9599.082    0.06       09599.082    0.06       010115.57    0.06       0
#XS Ineff= 2 , 0
       0                               0
Bank Sta=9599.082,10115.57
Exp/Cntr=0.3,0.1

Type RM Length L Ch R = 1 ,6896.264,241.512700,241.512700,241.512700
XS GIS Cut Line= 6
747869.642904123764063.843480107747941.870938776764149.380574671
748004.983015028764249.767664546748040.102752094764332.843110047
748061.489222172764428.522428597748087.429763759764490.275521733
#Sta/Elev= 30
9599.0961200.8299637.0071195.5539651.9571192.8779667.4441191.0739699.9711185.371
 9705.551184.0749717.9011178.7279742.0581175.0089754.136 1173.549766.2151170.725
 9778.211165.8289789.7291164.1959809.6621157.9979812.7661157.3339835.5741154.104
9853.0351150.9819871.8551149.006 9911.671141.2149953.3741136.8229963.7371133.414
9973.9341128.6519984.0981125.17210004.421123.32110024.961125.82610030.081127.392
10035.431129.71810045.551141.851   100571155.01110068.081158.03510085.431157.554
#Mann= 3 , 0 , 0
9599.096    0.06       09599.096    0.06       010085.43    0.06       0
#XS Ineff= 2 , 0
       0                               0
Bank Sta=9599.096,10085.43
Exp/Cntr=0.3,0.1

Type RM Length L Ch R = 1 ,6654.751,241.512600,241.512600,241.512600
XS GIS Cut Line= 6
747649.983185012764061.515211164747722.054345847764141.873666015
747758.811934886764199.264508506747781.371386443764245.996042179
747808.589186375764334.819115358747826.150062771 764495.40766613
#Sta/Elev= 30
9599.1381231.2599604.0491228.0299606.2571227.2979620.4481226.5449634.6391222.033
9672.4841213.9599696.0651212.7219712.3371205.5119735.3051198.8849747.0041196.323
9789.6271192.1139812.6291188.571 9847.461182.1279868.6931176.9829879.2631173.568
9889.5681168.6619910.1781160.2249940.7011149.4799950.8121144.7319960.9231138.358
9971.0341124.7369981.0591119.1839991.0761118.11810001.091115.899 10011.11115.541
10021.111116.65410031.121123.94510041.171134.46910051.22 1136.42 10082.11137.609
#Mann= 3 , 0 , 0
9599.138    0.06       09599.138    0.06       0 10082.1    0.06       0
#XS Ineff= 2 , 0
       0                               0
Bank Sta=9599.138,10082.1
Exp/Cntr=0.3,0.1

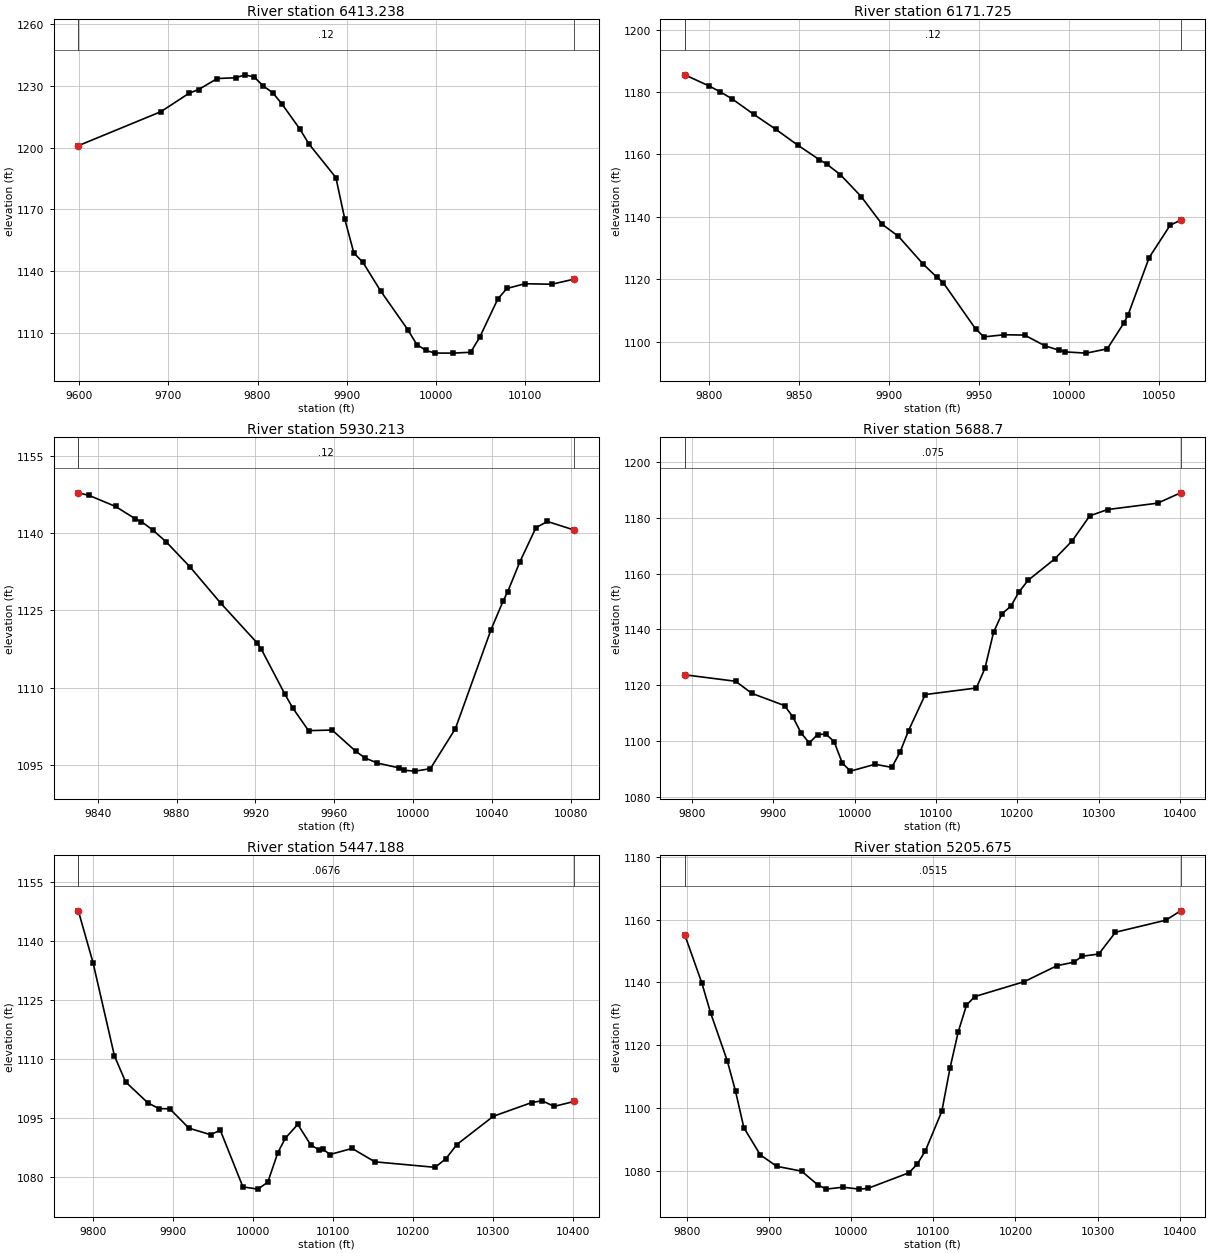
Type RM Length L Ch R = 1 ,6413.238,241.512700,241.512700,241.512700
XS GIS Cut Line= 6
747239.935671488764435.247021257747370.437881299764487.535058058
747479.878464157764514.069788512747647.826454629764535.621062489
747721.671704476764524.724996383747780.027532971764520.757351908
#Sta/Elev= 30
9599.0931200.9919691.6551217.5279723.4241226.5379734.0141228.3049754.8671233.653
9775.5971234.0249785.9621235.4499796.3281234.3689806.6541229.9249816.8581226.839
9827.0611221.4849847.4671209.0879857.6091201.8549887.8571185.506 9897.941165.144
9908.0231148.8199918.1061144.3239937.9261130.4359968.519  1111.59978.6021104.291
9988.6851101.4679998.7681100.14210018.931100.11410038.981100.52610049.111107.815
10069.421126.41910079.581131.54610099.861133.86110130.021133.61210155.051136.095
#Mann= 3 , 0 , 0
9599.093    0.12       09599.093    0.12       010155.05    0.12       0
#XS Ineff= 2 , 0
       0                               0
Bank Sta=9599.093,10155.05
Exp/Cntr=0.3,0.1

Type RM Length L Ch R = 1 ,6171.725,241.512600,241.512600,241.512600
XS GIS Cut Line= 6
747708.357288433764824.819545404747721.445531209 764810.49523812
747749.241291242764771.295968165747772.021214715764732.637672025
747816.750013201764647.887123785747851.095044412764589.998664741
#Sta/Elev= 30
9786.3161185.4999799.6181181.979 9805.721180.1359812.4561177.8489824.7151172.806
9836.9741168.0099849.2331162.8979861.0811158.3229865.1171156.9119872.6881153.549
9884.2951146.5099895.9021137.6419905.0261133.7449918.5881124.9429926.4511120.614
9929.8951118.9099947.8761104.097 9952.511101.5469963.8171102.2239975.1241102.111
9986.431 1098.679994.4741097.228 9997.791096.72210009.391096.33410021.031097.708
10030.361106.07510032.681108.70410044.321126.96610055.961137.30310061.791138.948
#Mann= 3 , 0 , 0
9786.316    0.12       09786.316    0.12       010061.79    0.12       0
#XS Ineff= 2 , 0
       0                               0
Bank Sta=9786.316,10061.79
Exp/Cntr=0.3,0.1

Type RM Length L Ch R = 1 ,5930.213,241.512700,241.512700,241.512700
XS GIS Cut Line= 6
747930.634899262764899.084888916747949.871028924764877.504748333
747970.369073407 764849.40184897748028.775644373764762.062124901
748058.959654663764726.631116656748085.285659428 764702.07560194
#Sta/Elev= 30
9830.2051147.7929835.677 1147.299849.0731145.1449859.1141142.7469862.2141142.195
9867.8171140.6049874.5911138.3369886.9691133.3469902.3691126.3889920.6611118.738
 9923.041117.3929934.9831108.6749938.9531106.0139946.9251101.6389958.8681101.753
9970.8111097.6519975.5371096.3379981.8141095.3469992.7271094.4199995.3211093.938
   100011093.78110008.681094.25810021.381102.02910039.451121.25710045.551126.774
10047.881128.591   100541134.35110062.181141.01710067.991142.23610081.581140.572
#Mann= 3 , 0 , 0
9830.205    0.12       09830.205    0.12       010081.58    0.12       0
#XS Ineff= 2 , 0
       0                               0
Bank Sta=9830.205,10081.58
Exp/Cntr=0.3,0.1

Type RM Length L Ch R = 1 ,  5688.7,241.512600,241.512600,241.512600
XS GIS Cut Line= 6
 747943.21526187764947.076486034748034.549809954764936.786632978
748176.494508933764956.100550245748253.366678231764974.738375653
748344.985288425765005.308762516748525.456683106765087.522526067
#Sta/Elev= 30
 9791.361123.7299853.7971121.417 9873.841117.0799913.9391112.7059924.0211108.747
9934.1911102.9689944.3611099.3179954.5311102.3239964.7011102.5099974.8711099.834
9984.974 1092.129995.0451089.229 10025.31091.68810045.851090.57110056.141096.158
10066.431103.75410087.011116.659 10149.81119.00410160.341126.05610170.881138.917
10181.421145.67610191.97 1148.2110202.491153.52710213.351157.56810245.881165.173
10267.561171.69810289.241180.67510311.181182.92410372.611185.209 10400.91188.911
#Mann= 3 , 0 , 0
 9791.36   0.075       0 9791.36   0.075       0 10400.9   0.075       0
#XS Ineff= 2 , 0
       0                               0
Bank Sta=9791.36,10400.9
Exp/Cntr=0.3,0.1

Type RM Length L Ch R = 1 ,5447.188,241.512700,241.512700,241.512700
XS GIS Cut Line= 6
747830.701292442764994.845468351747933.095326809765087.357440832
748012.373537471765139.923998827748080.263286677765195.266393915
748191.050363885765311.850552819748281.584263619765414.992804541
#Sta/Elev= 30
9781.9321147.7349800.251 1134.569827.0351110.7899840.9841104.1799868.8821098.828
9882.8311097.3799896.0931097.3489920.0381092.4179947.0341090.7489959.1531091.896
9987.3781077.46710006.131076.89710018.481078.67210030.941086.13910040.451089.887
10055.93 1093.3710072.151088.13510082.551086.897 10087.3 1087.1210095.861085.695
10123.741087.25910152.081083.84710227.291082.44710240.861084.63310254.431088.232
10300.031095.44110347.75 1098.9210361.061099.39210375.821097.95210400.961099.215
#Mann= 3 , 0 , 0
9781.932  0.0676       09781.932  0.0676       010400.96  0.0676       0
#XS Ineff= 2 , 0
       0                10078.96       0
Bank Sta=9781.932,10400.96
Exp/Cntr=0.3,0.1

Type RM Length L Ch R = 1 ,5205.675,241.512600,241.512600,241.512600
XS GIS Cut Line= 6
747796.796096974765005.720719737747813.153748914765064.582774589
747814.790904469765108.863169482747798.230220198 765276.54001809
747797.245354623765374.712474598747831.827002274765602.573764645
#Sta/Elev= 30
9797.7881155.0889818.5991139.7079829.0651130.3429849.4191115.0039859.5781105.242
9869.5851093.6969889.5991085.024 9909.641081.3579939.7921079.8299959.8931075.384
9969.944  1074.19990.0451074.70510010.141074.09310020.191074.30310070.421079.296
10080.431082.01310090.441086.30310110.451098.88110120.461112.71910130.461124.245
10140.461132.69310150.47 1135.44 10210.61140.18610250.841145.31510271.021146.394
10281.121148.29810301.38    114910321.691155.93910382.981159.78910400.961162.769
#Mann= 3 , 0 , 0
9797.788  0.0515       09797.788  0.0515       010400.96  0.0515       0
#XS Ineff= 2 , 0
       0                               0
Bank Sta=9797.788,10400.96
Exp/Cntr=0.3,0.1

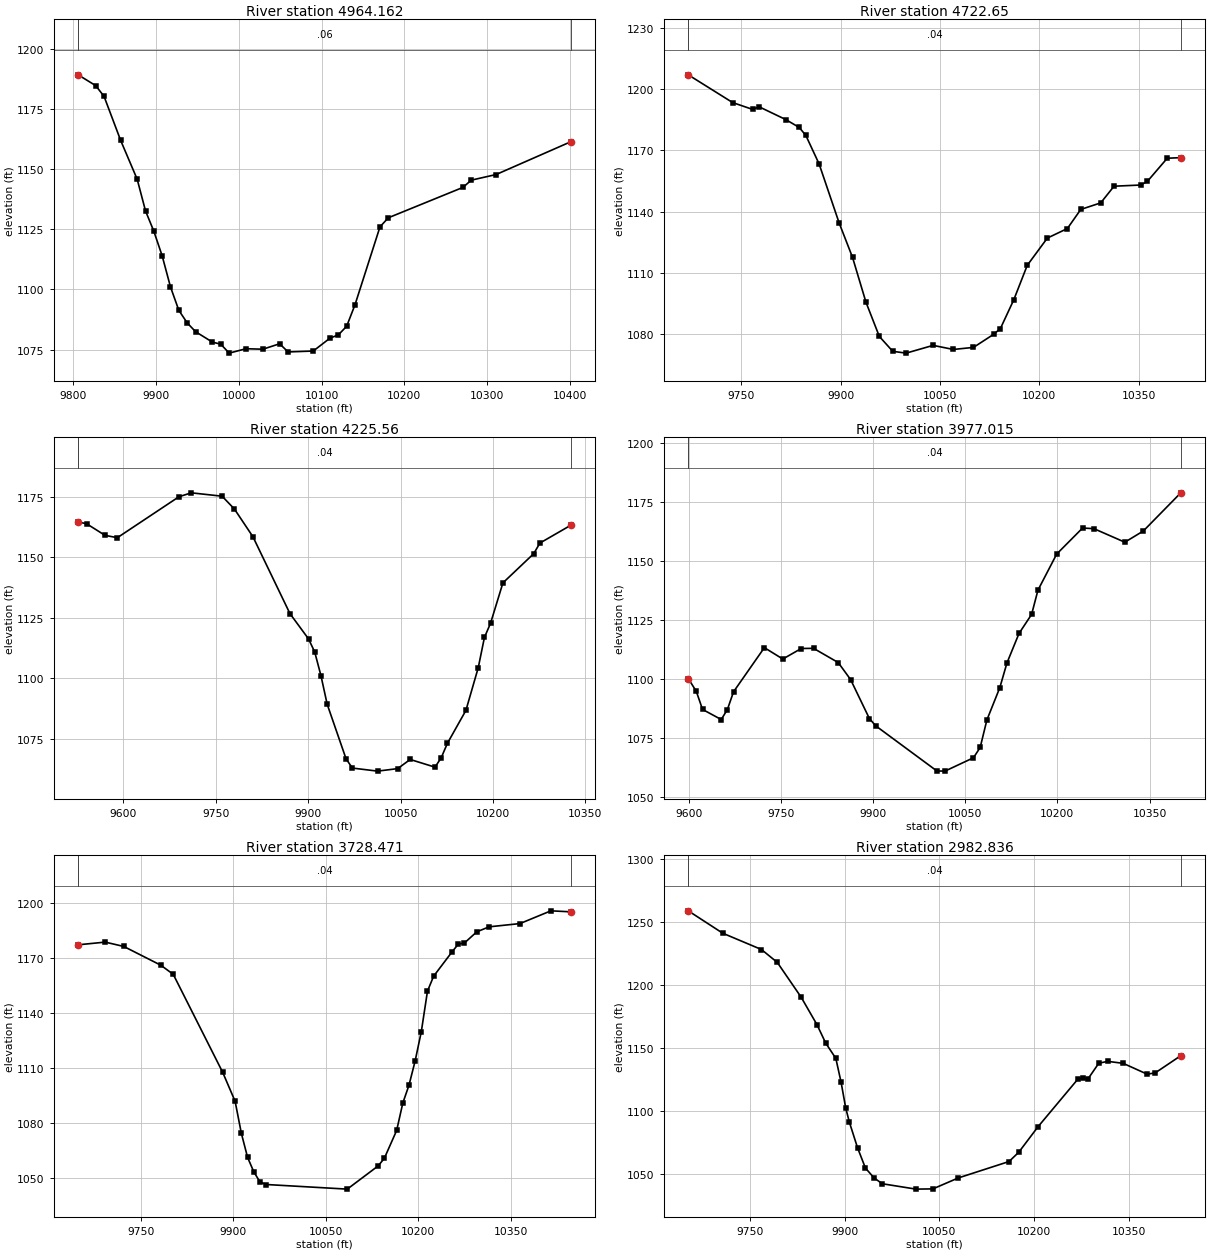
Type RM Length L Ch R = 1 ,4964.162,241.512700,241.512700,241.512700
XS GIS Cut Line= 6
747583.513205578764954.283731599747590.046787103765019.463452347
747586.799646867765059.638540588747554.957118434765246.822751566
747544.526387139765341.001939928747545.900902799765545.016949289
#Sta/Elev= 30
9806.0751189.0939827.2931184.5989837.3371180.1469857.352 1161.899877.382  1145.7
9887.4141132.5859897.447 1124.159907.4791113.9729917.5531101.0359927.6611091.284
 9937.771086.0779947.8791082.4229968.1481078.1029978.3111077.2349988.4741073.521
 10008.81075.354 10029.11075.14610049.411077.40810059.561074.01910090.021074.392
10110.251079.74910120.311081.09710130.37 1084.6910140.431093.61110170.621125.982
10180.681129.72810270.821142.34910280.821145.34610310.841147.68710400.931161.284
#Mann= 3 , 0 , 0
9806.075    0.06       09806.075    0.06       010400.93    0.06       0
#XS Ineff= 2 , 0
       0                               0
Bank Sta=9806.075,10400.93
Exp/Cntr=0.3,0.1

Type RM Length L Ch R = 1 , 4722.65,497.089400,497.089400,497.089400
XS GIS Cut Line= 6
747296.489929918764808.029829743747304.628867622764933.847577013
747316.524758898765037.143797066747362.902279093765303.450523819
747377.548433422765405.752542895747389.673699322765545.452917643
#Sta/Elev= 30
9669.8791206.9559736.9821193.3849767.0541190.0569777.078  1191.39817.2631185.067
9837.3951181.2489847.4611177.3499867.593 1163.339897.7911134.5329918.0161117.703
9938.2521095.8369958.4891079.0459978.7821071.773    99991070.88910039.781074.683
10070.261072.68610100.741073.68910131.221080.10310141.381082.898 10161.71097.052
10181.951113.81410212.26 1127.1310242.56 1131.8110262.771141.13710292.961144.356
10313.041152.50310353.211153.07310363.251154.80710393.381166.16710413.871166.474
#Mann= 3 , 0 , 0
9669.879    0.04       09669.879    0.04       010413.87    0.04       0
#XS Ineff= 2 , 0
       0                               0
Bank Sta=9669.879,10413.87
Exp/Cntr=0.3,0.1

Type RM Length L Ch R = 1 , 4225.56,248.544800,248.544800,248.544800
XS GIS Cut Line= 6
746897.727110886764751.375002995746897.816984399765096.541338432
746882.332679974765194.583031137746856.714479679765285.559890417
746846.595426891765396.772669615746843.414052719765544.980730365
#Sta/Elev= 30
9526.7051164.6669540.3351163.9419570.344 1159.129590.3481158.1629690.3651175.116
9710.3681176.7269760.3681175.3299780.3681170.0049810.3831158.547 9870.44 1126.75
9900.6281116.2739910.6931110.8349920.7581101.0889930.8791089.2469961.5551066.629
9971.7971062.81110012.741061.54610045.331062.58210065.641066.37210105.911063.189
10115.971067.065   101261073.03410156.081086.67310176.131104.37410186.141116.865
10196.151122.80710216.16 1139.4610266.191151.55510276.191155.93110326.171163.281
#Mann= 3 , 0 , 0
9526.705    0.04       09526.705    0.04       010326.17    0.04       0
#XS Ineff= 2 , 0
       0                               0
Bank Sta=9526.705,10326.17
Exp/Cntr=0.3,0.1

Type RM Length L Ch R = 1 ,3977.015,248.544700,248.544700,248.544700
XS GIS Cut Line= 6
746676.364639025764832.102547686746692.114181626764969.069095545
746683.863388319765104.265781287746663.237469474765178.536531629
746582.498671461765333.729848917746548.042477157765605.922847579
#Sta/Elev= 30
9599.1471100.1679612.2271094.7139622.3681087.045 9652.791082.7619662.8251086.985
9672.8581094.5319723.0221113.2689753.0691108.4339783.0711112.903 9803.081112.978
9843.249 1106.94 9863.421099.719 9893.97 1083.199904.1971080.10610003.811060.935
10017.021060.85710063.391066.52710074.331070.88910085.261082.55910106.351096.327
10117.911106.74710137.591119.302 10158.11127.38910168.361137.65110198.921152.992
10241.061164.03910259.541163.76410309.821158.019 10339.91162.76610400.921178.976
#Mann= 3 , 0 , 0
9599.147    0.04       09599.147    0.04       010400.92    0.04       0
#XS Ineff= 2 , 0
       0 9849.42                       0
Bank Sta=9599.147,10400.92
Exp/Cntr=0.3,0.1

Type RM Length L Ch R = 1 ,3728.471,745.634200,745.634200,745.634200
XS GIS Cut Line= 6
746371.001117045764831.297666455   746391.936186765088.488847761
746416.688873067765252.698311949 746420.52935373765320.688355502
746423.861019312765543.622158103746430.053860574 765626.98103813
#Sta/Elev= 30
9648.6611177.0479692.5081178.5119722.6071176.1479782.806 1165.899802.8721160.922
9883.1371107.3839903.2031091.6269913.2891074.2099923.4041061.0359933.5191053.143
9943.6341047.5539953.7491046.22710085.091043.70710135.171056.37710145.181060.513
10165.181075.72110175.181090.70410185.181100.42310195.181113.69210205.181129.671
10215.181151.77310225.18 1159.9310255.181173.25310265.181177.42910275.18 1178.06
10295.181184.13810315.191186.85610365.221188.63410415.341195.58710447.441195.046
#Mann= 3 , 0 , 0
9648.661    0.04       09648.661    0.04       010447.44    0.04       0
#XS Ineff= 2 , 0
       0                               0
Bank Sta=9648.661,10447.44
Exp/Cntr=0.3,0.1

Type RM Length L Ch R = 1 ,2982.836,0.000000,0.000000,0.000000
XS GIS Cut Line= 6
745496.648437735765110.069388268745556.981337596765196.821714511
745630.587462421765293.268319444 745678.86412553765351.292697324
745857.630381713765555.669837358745986.654287497765716.929431398
#Sta/Elev= 30
9652.3011258.7449707.0291240.9369768.2581228.0239793.4171217.7619831.1561190.172
9856.315 1168.299870.0851153.7099886.1941141.5039894.5571122.435 9901.831102.094
9907.5651090.9849920.5741070.514  9933.11054.3899946.5911046.6859959.725 1041.95
10013.191037.67610040.021037.87110080.251046.567 10160.71059.61110176.09    1067
10206.881087.415 10269.61124.96810277.091126.21110285.411124.95610302.91  1137.7
10317.031139.16510341.471137.61110379.581128.99110392.29 1130.0110432.851143.669
#Mann= 3 , 0 , 0
9652.301    0.04       09652.301    0.04       010432.85    0.04       0
#XS Ineff= 2 , 0
       0                               0
Bank Sta=9652.301,10432.85
Exp/Cntr=0.3,0.1